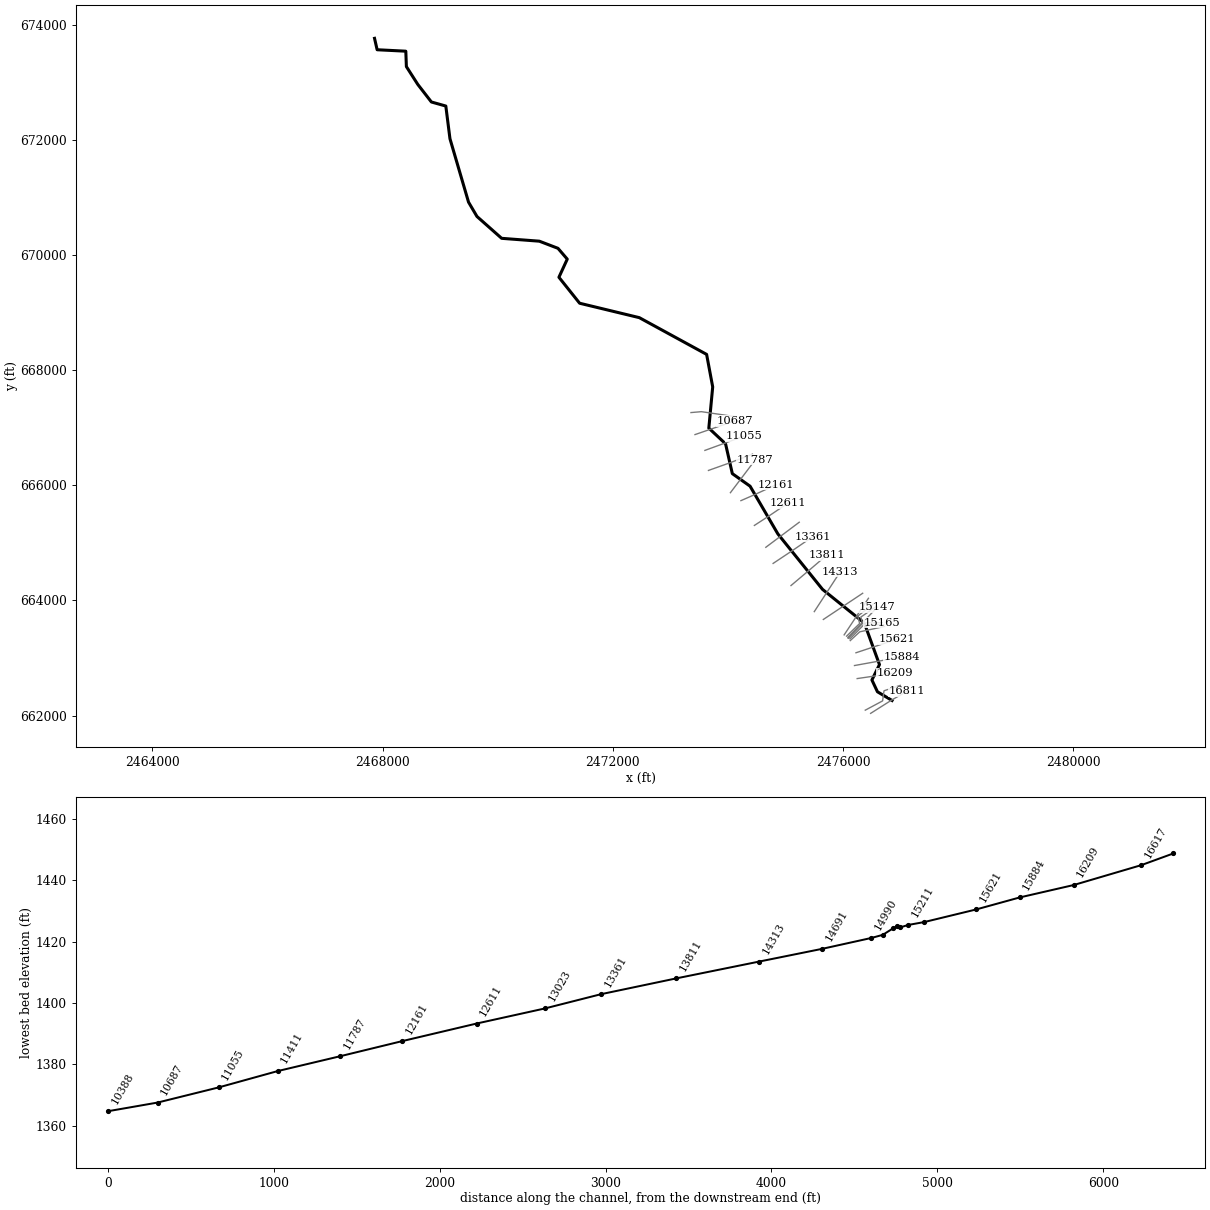
--- BRUSHRN1.prj (project) ---

Proj Title=BRUSHRN1
Current Plan=p01
Default Exp/Contr=0,0
English Units
Geom File=g01
Flow File=f01
Plan File=p01
BEGIN DESCRIPTION:
Stream Name: Brushy Run (1)
Flood Zone: Approximate
Pendleton County, West Virginia
HEC-RAS Version: 5.0.7
Hydrology Method:
Regression equation/Gage weighting
END DESCRIPTION:
DSS Export Rating Curves= 0
DSS Export Rating Curve Sorted= 0
DSS Export Volume Flow Curves= 0
DXF OffsetX= 0
DXF OffsetY= 0
DXF ScaleX= 0
DXF ScaleY= 0

--- BRUSHRN1.p01 (plan) ---

Plan Title=Floodplain
Program Version=5.07
Short Identifier=Floodplain
Geom File=g01
Flow File=f01
Subcritical Flow
K Sum by GR= 0
Std Step Tol= 0.01
Critical Tol= 0.01
Num of Std Step Trials= 20
Max Error Tol= 0.3
Flow Tol Ratio= 0.001
Split Flow NTrial= 30
Split Flow Tol= 0.02
Split Flow Ratio= 0.02
Log Output Level= 0
Friction Slope Method= 1
Unsteady Friction Slope Method= 2
Unsteady Bridges Friction Slope Method= 1
Parabolic Critical Depth
Global Vel Dist= 0 , 0 , 0
Global Log Level= 0
CheckData=True
Encroach Param=-1 ,0,0, 0
Mapping Interval=1HOUR
Computation Time Step Use Courant=        0
Computation Time Step Use Time Series=    0
Computation Time Step Count To Double=0
Computation Time Step Max Doubling=0
Computation Time Step Max Halving=0
Computation Time Step Residence Courant=0
Run HTab= 0
Run UNet= 0
Run Sediment= 0
Run PostProcess= 0
Run WQNet= 0
Run RASMapper= 0
UNET Theta= 0
UNET Theta Warmup= 0
UNET ZTol= 0
UNET ZSATol= 0
UNET MxIter= 0
UNET Max Iter WO Improvement= 0
UNET MaxInSteps= 0
UNET DtIC= 0
UNET DtMin= 0
UNET MaxCRTS= 0
UNET WFStab= 0
UNET SFStab= 0
UNET WFX= 1
UNET SFX= 1
UNET 1D Methodology=Finite Difference
UNET DSS MLevel= 1
UNET Pardiso=0
UNET DZMax Abort= 0
UNET Use Existing IB Tables= 0
UNET Froude Reduction=False
UNET Froude Limit= 0
UNET Froude Power= 0
UNET D1 Cores= 0
UNET D2 Coriolis=0
UNET D2 Cores= 0
UNET D2 Theta= 1
UNET D2 Theta Warmup= 1
UNET D2 Z Tol= 0.01
UNET D2 Volume Tol= 0.01
UNET D2 Max Iterations= 20
UNET D2 Equation= 0
UNET D2 RampUpFraction=0.1
UNET D2 TimeSlices= 1
UNET D2 BCVolumeCheck=0
UNET D1D2 MaxIter= 0
UNET D1D2 ZTol=0.01
UNET D1D2 QTol=0.1
UNET D1D2 MinQTol=1
Write IC File= 0
Write IC File at Fixed DateTime=0
Write IC File at Sim End=0
Echo Input=False
Echo Parameters=False
Echo Output=False
Write Detailed= 0
HDF Write Warmup=0
HDF Write Time Slices=0
HDF Flush=0
HDF Face Node Velocities=0
HDF Compression= 1
HDF Chunk Size= 1
HDF Spatial Parts= 1
HDF Use Max Rows=0
HDF Fixed Rows= 1
Calibration Method= 0
Calibration Iterations= 20
Calibration Max Change=0.05
Calibration Tolerance=0.2
Calibration Maximum=1.5
Calibration Minimum=0.5
Calibration Optimization Method= 1
WQ AD Non Conservative
WQ ULTIMATE=-1
WQ Max Comp Step=1HOUR
WQ Output Interval=15MIN
WQ Output Selected Increments= 0
WQ Output face flow=0
WQ Output face velocity=0
WQ Output face area=0
WQ Output face dispersion=0
WQ Output cell volume=0
WQ Output cell surface area=0
WQ Output cell continuity=0
WQ Output cumulative cell continuity=0
WQ Output face conc=0
WQ Output face dconc_dx=0
WQ Output face courant=0
WQ Output face peclet=0
WQ Output face adv mass=0
WQ Output face disp mass=0
WQ Output cell mass=0
WQ Output cell source sink temp=0
WQ Output nsm pathways=0
WQ Output nsm derived pathways=0
WQ Output MaxMinRange=-1
WQ Daily Max Min Mean=-1
WQ Daily Range=0
WQ Daily Time=0
WQ Create Restart=0
WQ Fixed Restart=0
WQ System Summary=0
WQ Write To DSS=0
WQ Use Fixed Temperature=0
Sorting and Armoring Iterations= 10
XS Update Threshold= 0.02
Bed Roughness Predictor= 0
Hydraulics Update Threshold= 0.02
Energy Slope Method= 1
Volume Change Method= 1
Sediment Retention Method= 0
XS Weighting Method= 0
Number of US Weighted Cross Sections= 1
Number of DS Weighted Cross Sections= 1
Upstream XS Weight=0
Main XS Weight=1
Downstream XS Weight=0
Number of DS XS's Weighted with US Boundary= 1
Upstream Boundary Weight= 1
Weight of XSs Associated with US Boundary= 0
Number of US XS's Weighted with DS Boundary= 1
Downstream Boundary Weight= 0.5
Weight of XSs Associated with DS Boundary= 0.5
Percentile Method= 0
Sediment Output Level= 3
Mass or Volume Output= 0
Output Increment Type= 1
Profile and TS Output Increment= 1
XS Output Flag= 0
XS Output Increment= 10
Write Gradation File= 0
Read Gradation Hotstart= 0
Write HDF5 File= 1
Write Binary Output= 1
Write DSS Sediment File= 0
SV Curve= 0
Specific Gage Flag= 0

--- BRUSHRN1.f01 (steady flow) ---

Flow Title=Flows
Program Version=5.07
Number of Profiles= 6
Profile Names=P100yr,P10yr,P25yr,P50yr,P500yr,P101yr
River Rch & RM=BRUSHRN1,Main            ,16811
     909     393     580     739    1377    1199
River Rch & RM=BRUSHRN1,Main            ,14990
    1022     445     654     832    1545    1335
River Rch & RM=BRUSHRN1,Main            ,11411
    1154     506     740     940    1741    1494
River Rch & RM=BRUSHRN1,Main            ,9911
    1503     666     968    1227    2261    1915
River Rch & RM=BRUSHRN1,Main            ,8111
    1671     743    1078    1365    2511    2117
River Rch & RM=BRUSHRN1,Main            ,0
    2918    1311    1890    2388    4378    3618
Boundary for River Rch & Prof#=BRUSHRN1,Main            , 1
Up Type= 0
Dn Type= 1
Dn Known WS=1259.25
Boundary for River Rch & Prof#=BRUSHRN1,Main            , 2
Up Type= 0
Dn Type= 1
Dn Known WS=1257.33
Boundary for River Rch & Prof#=BRUSHRN1,Main            , 3
Up Type= 0
Dn Type= 1
Dn Known WS=1258.21
Boundary for River Rch & Prof#=BRUSHRN1,Main            , 4
Up Type= 0
Dn Type= 1
Dn Known WS=1258.93
Boundary for River Rch & Prof#=BRUSHRN1,Main            , 5
Up Type= 0
Dn Type= 1
Dn Known WS=1259.95
Boundary for River Rch & Prof#=BRUSHRN1,Main            , 6
Up Type= 0
Dn Type= 1
Dn Known WS=1259.61
DSS Import GetInterval= 0
DSS Import GetPeak= 0
DSS Import FillOption= 0

--- BRUSHRN1.g01 (geometry) ---

Geom Title=Geometry
Program Version=5.07

River Reach=BRUSHRN1        ,Main
Reach XY= 30
2476848.55062059662261.7218946672476594.74497128662413.371105596
2476498.65440702662618.0713877832476629.78628778662885.445087388
2476367.12264869663606.6369139852475641.14744493664191.469798222
2474864.38653517665156.2337095592474382.24823493665984.388736576
 2474073.9461605666202.4234226352473956.35659611666720.528812274
 2473665.6348469666992.921047553 2473733.0461317667708.637826815
 2473627.2057839668273.7792951022472458.19306296668911.881932333
2471421.57171986669162.2686755512471061.82838938669613.464598089
2471206.71957353 669928.383524092471045.63951644670116.078824699
2470721.52694067 670240.084156932470067.10464311670289.730036899
2469638.30136651670669.2637994292469492.03713667670917.953638747
2469169.06174022672020.407388732 2469097.2259168672587.543396324
2468846.49516588672658.100866556 2468609.8647947672963.749386102
2468412.17987999673272.7311839012468402.15937576673540.297440737
2467904.24049556 673565.420420172467858.90970787673763.631603837

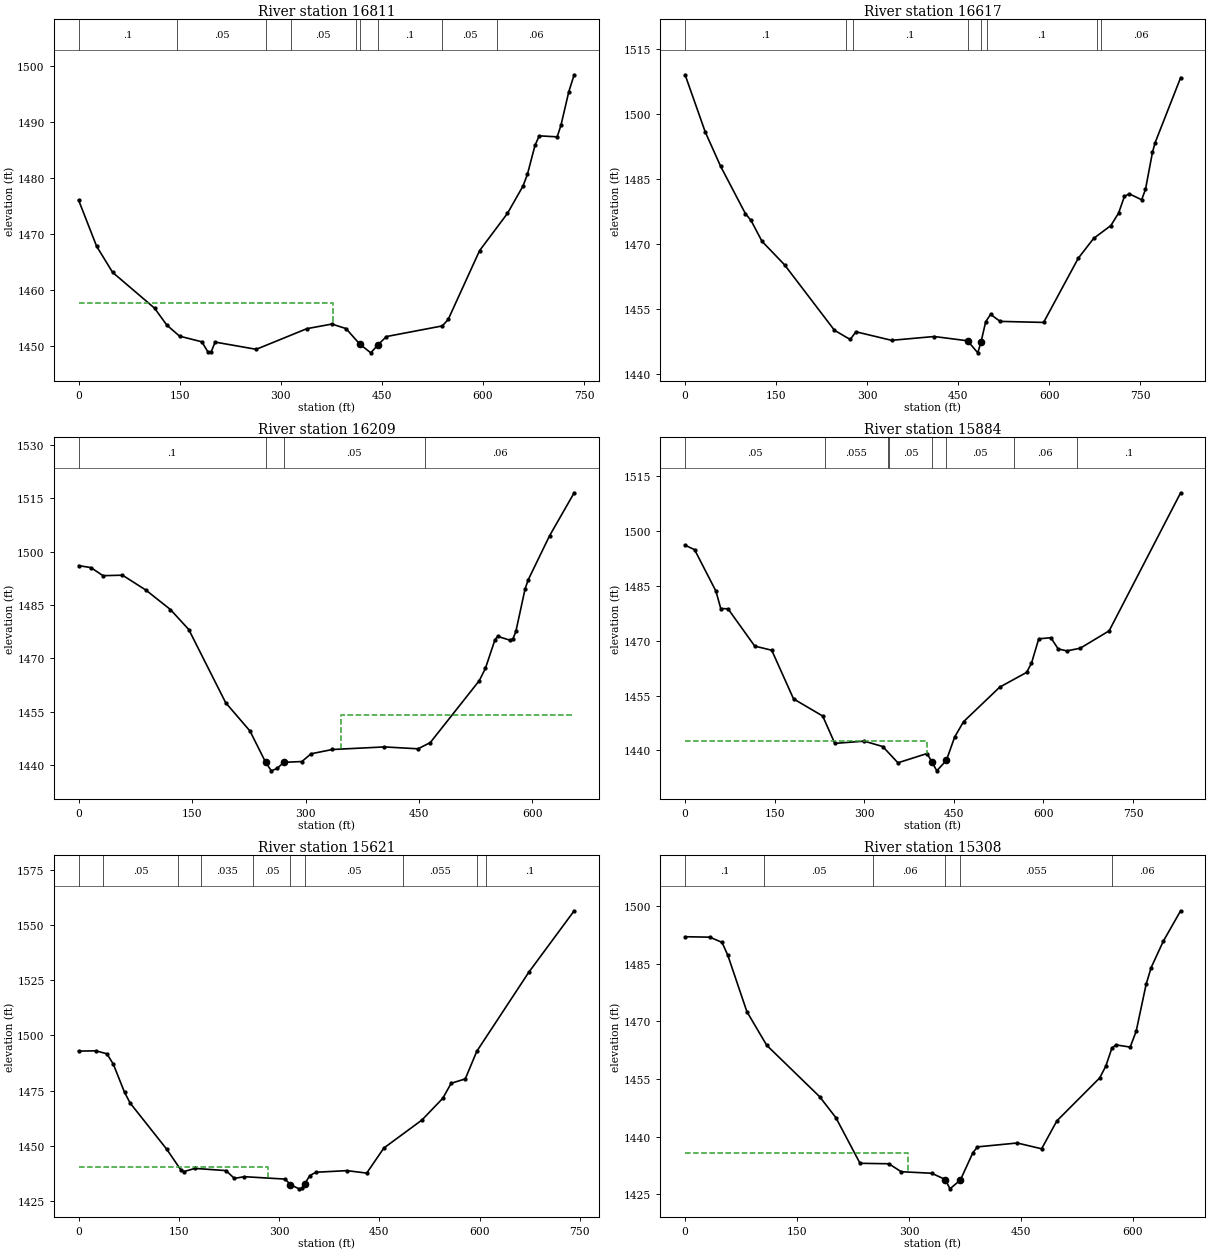
Type RM Length L Ch R = 1 ,16811   ,174.8,194.2,205.6
XS GIS Cut Line= 3
2476476.16605524662038.014012245     2476843.698      662270.466
2477104.63920453662419.735257687
#Sta/Elev= 30
       0 1476.05    26.7 1467.82    50.4 1463.16   112.7 1456.76   130.8 1453.75
   149.8 1451.76   182.9 1450.75   192.4 1448.85   196.8 1448.97   202.6  1450.7
   263.6 1449.41   338.8  1453.1   375.8 1453.92   396.8 1453.12   417.6  1450.3
   433.7 1448.78   443.8 1450.15   456.8 1451.69   539.8 1453.59   548.5 1454.74
   595.1 1467.04   636.5  1473.7   659.6 1478.59   666.1 1480.67   677.4 1485.87
   683.7 1487.55   710.3 1487.37   715.9 1489.45   727.6 1495.47   735.5 1498.46
#Mann= 9 ,-1 , 0
       0      .1       0  146.06     .05       0  278.71      .1       0
  314.57     .05       0  411.35      .1       0   417.6    .045       0
   443.8      .1       0  539.98     .05       0   620.7     .06       0
#XS Ineff= 2 , 0
           376.9 1457.65
Permanent Ineff=
       F       F
Bank Sta=417.6,443.8
XS Rating Curve= 0 ,0
Exp/Cntr=0.3,0.1

Type RM Length L Ch R = 1 ,16617   ,427.9,407.2,390.7
XS GIS Cut Line= 4
2476383.13252637662093.5147975512476684.29637763662254.985090107
2476708.59190802662430.467205139 2476990.7769773 662523.98830112
#Sta/Elev= 30
       0 1509.14    33.2 1495.93    58.6 1487.99    99.4 1477.06   108.5 1475.54
   126.6 1470.71   163.8 1465.27     246 1450.16   271.9 1448.03   281.4 1449.81
     340 1447.84   410.3 1448.72   465.3 1447.73   482.1 1444.95   487.4 1447.45
   495.1 1452.13   503.2 1453.83   518.9 1452.21   590.5 1451.97   647.5 1466.77
   672.8 1471.35   701.3 1474.34     714 1477.21   723.7  1481.1   731.8 1481.64
     752 1480.29   758.3 1482.69   769.8 1491.24   774.1 1493.44   816.2 1508.48
#Mann= 8 ,-1 , 0
       0      .1       0  264.46     .05       0  276.31      .1       0
   465.3    .045       0   487.4      .1       0  497.43      .1       0
  678.31      .1       0  685.55     .06       0
Bank Sta=465.3,487.4
XS Rating Curve= 0 ,0
Exp/Cntr=0.3,0.1

Type RM Length L Ch R = 1 ,16209   ,323.3,325.6,319.8
XS GIS Cut Line= 2
2476242.64340899662642.4831843542476890.94809698662737.490520245
#Sta/Elev= 30
       0 1496.05    16.3 1495.48    32.2 1493.22      58 1493.36      89 1489.17
   121.4 1483.72   145.6 1478.12   194.4 1457.59   226.5 1449.66   247.3 1440.85
   254.8 1438.47   262.9 1439.19     271 1440.86   295.2 1441.08   307.3 1443.25
   335.6 1444.46   404.4 1445.18   448.8 1444.65     465 1446.41   529.7 1463.76
   537.8  1467.2   550.5 1475.26     554 1476.19   570.1 1475.14   574.2 1475.45
   578.2 1477.66   590.3 1489.51   594.4 1492.05   622.7 1504.43   655.2 1516.48
#Mann= 4 ,-1 , 0
       0      .1       0   247.3    .045       0     271     .05       0
  457.91     .06       0
#XS Ineff= 2 , 0
                          346.62         1454.22
Permanent Ineff=
       F       F
Bank Sta=247.3,271
XS Rating Curve= 0 ,0
Exp/Cntr=0.3,0.1

Type RM Length L Ch R = 1 ,15884   ,260.4,262.8,265.3
XS GIS Cut Line= 2
2476196.01488465662868.953623347      2477012.51      663016.883
#Sta/Elev= 30
       0 1496.19    15.9 1494.96    51.6 1483.62    59.7 1478.86    71.9 1478.77
   116.6 1468.57   145.1 1467.43   181.6 1454.11   230.4 1449.43   250.7 1441.94
     300 1442.55     331 1441.07   356.4 1436.62   405.2 1439.16   413.6 1436.77
   421.5 1434.42   437.7 1437.33   437.7 1437.37   451.4 1443.68   466.2 1447.86
   526.9 1457.34   571.9 1461.37     580 1463.87   592.2 1470.56   612.5 1470.86
   624.7  1467.8   639.1 1467.26   661.6 1467.98   710.1 1472.75   829.8 1510.54
#Mann= 8 ,-1 , 0
       0     .05       0  234.34    .055       0  339.68    .035       0
  341.15     .05       0   413.6    .045       0   437.7     .05       0
  550.37     .06       0  655.71      .1       0
#XS Ineff= 2 , 0
          405.46  1442.6
Permanent Ineff=
       F       F
Bank Sta=413.6,437.7
XS Rating Curve= 0 ,0
Exp/Cntr=0.3,0.1

Type RM Length L Ch R = 1 ,15621   ,313.5,313,310.3
XS GIS Cut Line= 2
2476221.50283637663090.707715737     2476925.489      663324.341
#Sta/Elev= 30
       0 1492.89      26 1493.01    42.3 1491.67    51.9 1486.99    68.7 1474.21
    77.2 1469.32     132 1448.38     153 1439.07   157.2 1438.29   174.1 1439.76
   220.5 1438.76   233.1 1435.23   247.9    1436     309 1434.92   317.1 1432.39
     330  1430.5   334.3 1430.77   338.5 1432.77     346 1436.52   355.3 1438.02
   401.7 1438.74   431.2 1437.63   456.8 1448.97   513.8 1461.66     545  1471.5
   557.6 1478.32   578.7 1480.29     596 1492.83   673.6 1528.53   741.7 1556.45
#Mann= 10 ,-1 , 0
       0      .1       0   36.81     .05       0  148.84    .055       0
  183.08    .035       0  260.88     .05       0   317.1    .045       0
   338.5     .05       0  484.95    .055       0  596.98     .06       0
  610.04      .1       0
#XS Ineff= 2 , 0
          283.81 1440.48
Permanent Ineff=
       F       F
Bank Sta=317.1,338.5
XS Rating Curve= 0 ,0
Exp/Cntr=0.3,0.1

Type RM Length L Ch R = 1 ,15308   ,99.7,96.6,93.6
XS GIS Cut Line= 3
2476122.39809406663302.2496870752476287.33871991663454.661065397
2476716.76004299663547.775648254
#Sta/Elev= 30
       0 1492.05    33.1 1491.94    49.5 1490.58    57.3 1487.19    82.8 1472.53
   109.4 1463.77   180.2 1450.41     202 1444.94   234.4 1433.04   273.1 1432.92
   289.5 1430.85   330.4 1430.45   348.7 1428.82   354.9 1426.39   368.9  1428.7
   385.7 1435.83   391.8 1437.32     445 1438.33   477.7 1436.82   498.2  1444.1
   555.5 1455.27   563.7 1458.33   571.9 1463.06   577.4 1463.88   596.4 1463.31
   604.4 1467.42   617.8 1479.69   624.5 1484.03   640.9 1490.93     664 1498.81
#Mann= 6 ,-1 , 0
       0      .1       0  105.44     .05       0  252.38     .06       0
   348.7    .045       0   368.9    .055       0  572.49     .06       0
#XS Ineff= 2 , 0
          298.49 1435.75
Permanent Ineff=
       F       F
Bank Sta=348.7,368.9
XS Rating Curve= 0 ,0
Exp/Cntr=0.5,0.3

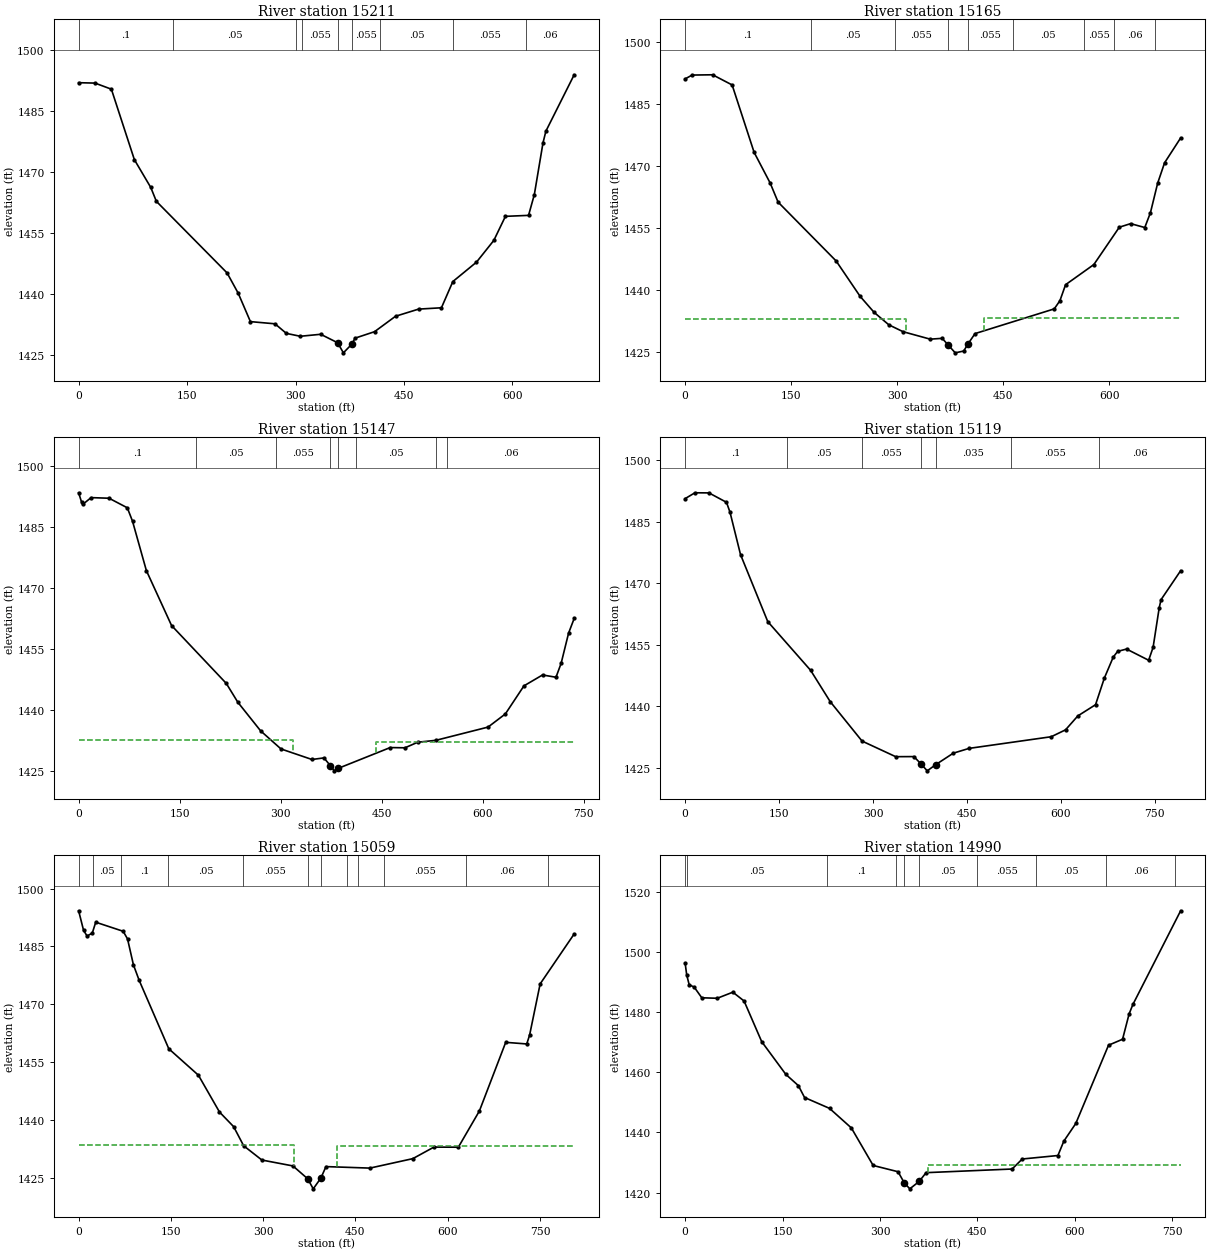
Type RM Length L Ch R = 1 ,15211   ,44,46,43
XS GIS Cut Line= 3
2476116.49356644 663333.089566442476354.17833645663572.945070828
2476701.89260904663578.009728519
#Sta/Elev= 30
       0 1491.99    22.7 1491.89    45.3 1490.39    77.1 1473.03    99.8 1466.18
   107.5 1462.77   205.3 1445.14   220.7 1440.14   237.6 1433.14   271.6  1432.6
   287.3 1430.24   306.6 1429.53   334.8 1430.02   358.2 1427.94   366.2 1425.45
   378.2 1427.65   382.2 1429.06   409.3 1430.66   438.3 1434.46   470.2 1436.22
   501.8 1436.55   517.6 1443.01   550.3 1447.79   574.3 1453.15   590.3 1459.07
   622.3 1459.31   630.3 1464.43   642.3 1477.19   646.3 1480.06   685.4 1493.94
#Mann= 9 ,-1 , 0
       0      .1       0  130.36     .05       0  301.25     .06       0
  309.17    .055       0   358.2    .045       0   378.2    .055       0
  417.04     .05       0   517.9    .055       0  618.76     .06       0
#XS Ineff= 2 , 0
          336.79    1427  391.48            1427
Permanent Ineff=
       F       F
Bank Sta=358.2,378.2
XS Rating Curve= 0 ,0
Exp/Cntr=0.5,0.3

Type RM Length L Ch R = 1 ,15165   ,9.2,18.3,35.2
XS GIS Cut Line= 3
2476091.89524832663343.7663878112476348.32741395663612.654525509
 2476677.4952601663612.654525509
#Sta/Elev= 30
       0 1490.98     9.9 1491.91    38.9 1491.98    66.5 1489.52    97.6  1473.2
   120.2 1465.81   131.5 1461.16   213.6 1446.91   247.5 1438.35   267.3 1434.47
   288.1 1431.46   308.3 1429.79   346.6 1427.99   363.6 1428.19   371.81426.607
     382 1424.68     394 1425.12   399.7 1426.76     410 1429.34     522 1435.32
     530  1437.3     538 1441.17     578 1446.05     614 1455.09     630 1455.95
     650 1455.01     658  1458.6   668.2 1465.74     678 1470.68   700.7 1476.69
#Mann= 9 ,-1 , 0
       0      .1       0  177.94     .05       0  296.74    .055       0
   371.8    .045       0   399.7    .055       0  463.02     .05       0
  563.63    .055       0  606.88     .06       0  664.24      .1       0
#XS Ineff= 2 , 0
          312.66 1432.88  422.94         1433.04
Permanent Ineff=
       F       F
Bank Sta=371.8,399.7
XS Rating Curve= 0 ,0
Exp/Cntr(USF)=0,0
Exp/Cntr=0.5,0.3

Type RM Length L Ch R = 1 ,15147   ,9.7,27.7,46.6
XS GIS Cut Line= 2
2476083.57715652663347.851354009 2476590.9172589663880.960608438
#Sta/Elev= 30
       0 1493.38     4.4 1491.06     7.2 1490.67    18.5 1492.19    45.2 1492.04
    72.3 1489.69      80 1486.41   100.6 1474.26     138 1460.76   219.3 1446.53
   236.4 1441.91   270.3 1434.87   300.5 1430.43   346.5 1427.84   364.3 1428.23
   373.91426.313   379.7 1425.05   385.2 1425.64   462.7 1430.77   484.6 1430.71
   503.6 1432.08   530.6 1432.55     608  1435.8   633.7 1439.03   661.3 1445.93
   688.9 1448.61   708.9 1448.05   716.5 1451.45   727.6 1458.89   735.9 1462.49
#Mann= 8 ,-1 , 0
       0      .1       0  174.45     .05       0  293.17    .055       0
   373.9    .045       0   385.2    .055       0  411.88     .05       0
   530.6    .055       0  547.74     .06       0
#XS Ineff= 2 , 0
          317.81 1432.68  441.55         1432.25
Permanent Ineff=
       F       F
Bank Sta=373.9,385.2
XS Rating Curve= 0 ,0
Exp/Cntr(USF)=0,0
Exp/Cntr=0.5,0.3

Type RM Length L Ch R = 1 ,15119   ,66.6,60.6,58.2
XS GIS Cut Line= 4
2476082.34410013663359.6856629272476333.15585346663615.596128558
 2476305.8684945663710.7218951642476581.32521177663899.812989263
#Sta/Elev= 30
       0 1490.62    15.7 1492.05    38.1 1492.02    66.1 1489.73    71.7 1487.33
    88.5    1477     132 1460.67   200.5 1448.79   231.7 1441.18   282.6 1431.56
   336.3 1427.76   365.4 1427.78   377.1 1425.94   386.7 1424.31   400.5 1425.84
   428.3 1428.61   453.5 1429.78   584.8 1432.62   607.6  1434.3   627.2 1437.69
   655.5 1440.42   669.6 1446.92   683.8 1452.03   690.8 1453.41     705 1453.98
   740.3 1451.25   747.4 1454.38   757.2 1464.05   760.1 1466.01   791.4 1473.06
#Mann= 7 ,-1 , 0
       0      .1       0  162.12     .05       0  282.07    .055       0
   377.1    .045       0   400.5    .035       0  520.37    .055       0
  661.76     .06       0
#XS Ineff= 2 , 0
          363.13    1427  418.61            1427
Permanent Ineff=
       F       F
Bank Sta=377.1,400.5
XS Rating Curve= 0 ,0
Exp/Cntr=0.5,0.3

Type RM Length L Ch R = 1 ,15059   ,79.4,68.4,53.2
XS GIS Cut Line= 4
2476058.74850128663379.5600848242476285.42976377663599.212268396
2476252.35597462 663726.878502172476534.32978794663947.616404066
#Sta/Elev= 30
       0 1494.24       8 1489.18    13.7 1487.71    22.2 1488.46    27.8 1491.28
    72.4 1488.93    79.5 1486.95    89.1 1480.23    98.5 1476.19   146.6  1458.5
   194.7 1451.66     229 1442.12     252 1438.33   268.3 1433.38   297.9 1429.69
   348.4 1428.16   372.31424.848   381.4 1422.23   393.8 1425.01   402.1 1427.99
   473.5  1427.6   543.3 1430.05   577.6 1433.04   617.3 1433.01   651.5 1442.39
   694.3 1460.17   728.5 1459.75   733.1 1462.02   750.3 1475.31   805.6 1488.24
#Mann= 12 ,-1 , 0
       0      .1       0    22.9     .05       0   68.41      .1       0
  145.15     .05       0   267.4    .055       0   372.3    .045       0
   393.8    .035       0  435.94     .05       0   454.4    .035       0
  496.17    .055       0  629.79     .06       0  763.41      .1       0
#XS Ineff= 2 , 0
          349.41 1433.66  420.49         1433.29
Permanent Ineff=
       F       F
Bank Sta=372.3,393.8
XS Rating Curve= 0 ,0
Exp/Cntr(USF)=0,0
Exp/Cntr=0.5,0.3

Type RM Length L Ch R = 1 ,14990   ,306.2,299.6,292.2
XS GIS Cut Line= 2
2476016.56532254663401.6573876832476438.13517328664037.406294436
#Sta/Elev= 30
       0 1496.36     2.5 1492.33     6.3 1489.08      14  1488.3    25.7 1484.75
    49.5 1484.59    73.5 1486.61    90.8 1483.68   117.9 1470.17   155.1 1459.27
   174.3 1455.56   183.9 1451.59   222.3 1447.98   255.9 1441.48   289.5 1428.99
   327.8 1426.91   337.2 1423.28   345.9 1421.22   360.3 1423.68     371  1426.6
   503.4 1427.81     519 1431.14   573.9  1432.3     583 1437.08   601.4 1442.95
   651.8 1468.98   673.4 1470.96   683.5  1479.4   689.3 1482.52   762.8 1513.68
#Mann= 10 ,-1 , 0
       0      .1       0     3.2     .05       0  217.96      .1       0
  325.34     .05       0   337.2    .045       0   360.3     .05       0
  449.76    .055       0  540.09     .05       0  647.47     .06       0
  754.85     .12       0
#XS Ineff= 2 , 0
                          373.99         1429.05
Permanent Ineff=
       F       F
Bank Sta=337.2,360.3
XS Rating Curve= 0 ,0
Exp/Cntr=0.3,0.1

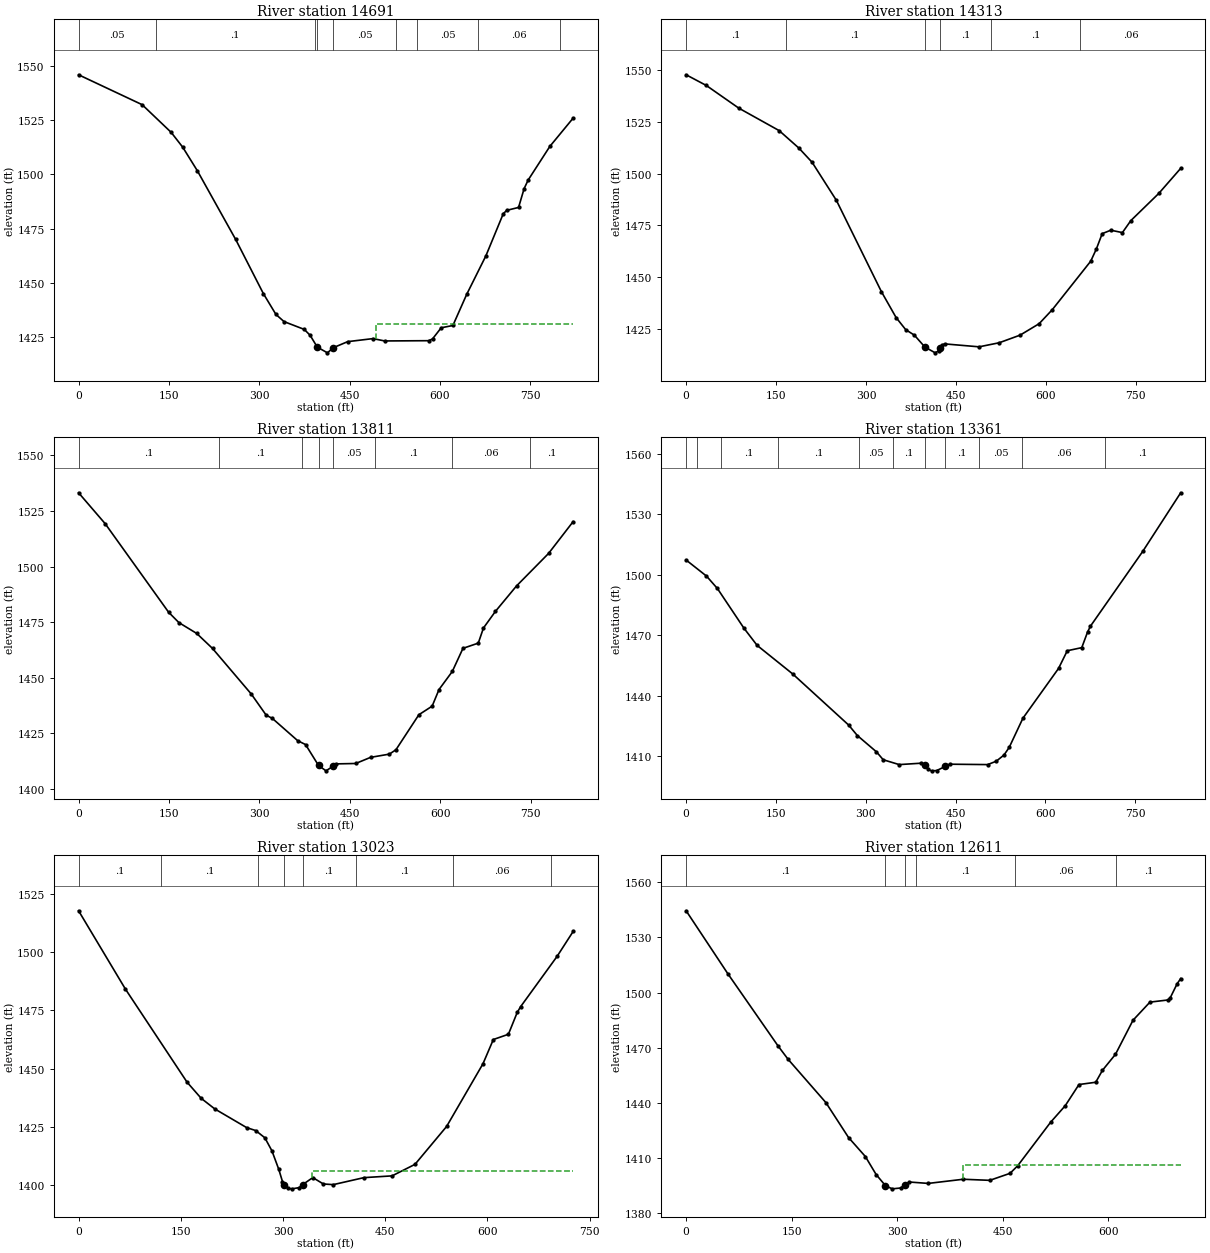
Type RM Length L Ch R = 1 ,14691   ,368.5,377.9,383.6
XS GIS Cut Line= 2
     2475654.898       663669.32     2476338.235      664124.294
#Sta/Elev= 30
       0 1546.05   105.5 1532.24   153.6 1519.48   172.8 1512.63   197.2  1501.7
   260.7 1470.03   306.8 1444.95   327.6 1435.37     341 1432.07   374.6 1428.46
   384.3 1425.75   396.2 1420.28   413.1 1417.64   422.7 1420.01   446.7 1422.81
   488.6 1424.21   508.1 1423.13   581.3 1423.25   587.5 1424.08   601.9 1429.21
   621.3 1430.27   644.3 1444.69   676.1 1462.45   704.9 1481.88   710.7 1483.45
   730.3 1484.78   739.5 1493.46   746.2 1497.43   782.3    1513   820.9 1526.03
#Mann= 9 ,-1 , 0
       0     .05       0  128.12      .1       0  391.92     .05       0
   396.2    .045       0   422.7     .05       0  527.42    .035       0
  561.38     .05       0  662.92     .06       0  798.42      .1       0
#XS Ineff= 2 , 0
                          493.63         1430.74
Permanent Ineff=
       F       F
Bank Sta=396.2,422.7
XS Rating Curve= 0 ,0
Exp/Cntr=0.3,0.1

Type RM Length L Ch R = 1 ,14313   ,507.8,502.1,497.7
XS GIS Cut Line= 2
     2475497.581      663805.365     2475947.551      664496.617
#Sta/Elev= 30
       0 1547.63    33.7 1542.47    87.7 1531.56   155.2 1520.69     188 1512.29
   210.1 1505.42   250.6 1487.06   325.7    1443   350.2 1430.52   366.2 1424.69
   380.7 1422.03   398.1 1416.33   415.4 1413.51   421.1 1414.52     424 1415.98
   426.6 1417.29   431.4 1417.82   488.6 1416.41   522.1 1418.37     557 1422.05
   588.7 1427.56   610.7 1434.34   674.8 1457.73   684.2 1463.64   693.9    1471
   708.2 1472.66   727.6 1471.51   741.6 1477.27   788.3 1490.41   824.8 1502.49
#Mann= 6 ,-1 , 0
       0      .1       0  165.84      .1       0   398.1    .045       0
     424      .1       0  508.76      .1       0  657.02     .06       0
Bank Sta=398.1,424
XS Rating Curve= 0 ,0
Exp/Cntr=0.3,0.1

Type RM Length L Ch R = 1 ,13811   ,451.4,450,446.7
XS GIS Cut Line= 3
     2475093.021      664258.249     2475406.925      664523.183
2475718.17189161664789.093132477
#Sta/Elev= 30
       0 1533.21    44.1 1519.29   149.3 1479.42   166.3 1474.76   195.9 1469.87
   222.1 1463.11   286.3 1442.61     311  1433.1   321.5 1431.57   363.4 1421.57
   376.4 1419.83   397.9 1410.42   410.3    1408   422.6 1410.18   427.5 1411.13
   459.6 1411.31   484.2 1414.07   515.4 1415.53   526.3 1417.51   564.3 1433.27
   586.3 1437.13   597.7 1444.62   619.7 1452.74   637.4 1463.16   662.8 1465.51
   671.4 1472.33   691.3 1479.83   726.2 1491.26   779.3 1505.88   820.1 1520.23
#Mann= 8 ,-1 , 0
       0      .1       0  233.27      .1       0  370.04     .05       0
   397.9    .045       0   422.6     .05       0  491.36      .1       0
  619.95     .06       0  748.53      .1       0
Bank Sta=397.9,422.6
XS Rating Curve= 0 ,0
Exp/Cntr=0.3,0.1

Type RM Length L Ch R = 1 ,13361   ,335.8,337.6,338.3
XS GIS Cut Line= 3
     2474782.462      664642.774        2475124.      664870.168
2475467.14110839665104.866771177
#Sta/Elev= 30
       0 1507.29      34 1499.34    52.2  1493.2    96.4  1473.6   118.6 1465.01
   178.1 1450.85   271.5 1425.55   285.9 1420.39   317.8 1412.32   329.2 1408.38
   355.9 1405.98   392.6 1406.68   399.2 1405.55   404.2 1403.59   409.9 1402.89
   418.5 1403.03   432.8 1405.08   439.9 1406.18   503.7 1405.98   517.9 1407.65
   530.8 1410.69   539.6  1414.5   562.5 1428.95     622  1453.6   636.6 1462.37
   660.8  1463.9   670.5 1471.65   675.3 1474.54   762.6 1511.55     826 1540.59
#Mann= 11 ,-1 , 0
       0      .1       0   17.93      .1       0   57.44      .1       0
  153.43      .1       0  288.93     .05       0  346.28      .1       0
   399.2    .045       0   432.8      .1       0  489.63     .05       0
  561.69     .06       0  698.78      .1       0
Bank Sta=399.2,432.8
XS Rating Curve= 0 ,0
Exp/Cntr=0.3,0.1

Type RM Length L Ch R = 1 ,13023   ,412.7,412.4,410.1
XS GIS Cut Line= 2
2474655.77750622664922.957446007     2475236.445      665358.308
#Sta/Elev= 30
       0 1517.91    68.7 1484.22   159.2 1444.14   179.9  1437.2   199.9 1432.63
   246.6  1424.6   259.9 1423.33   273.3 1420.23   283.7 1414.61   293.7 1406.68
   299.2 1401.38   302.1 1399.97   307.8 1398.42   313.3 1398.25   323.7 1398.78
   328.7 1400.05   343.7 1403.09   359.2 1400.34   373.7 1400.06   418.7 1403.07
     460 1403.83   493.6 1408.78     540 1425.08   593.4 1452.08   608.6 1462.51
   630.7 1464.76   643.6 1474.14   648.6 1476.63   702.1 1498.27   725.7 1509.01
#Mann= 8 ,-1 , 0
       0      .1       0  120.67      .1       0  263.82      .1       0
   302.1    .045       0   328.7      .1       0  406.97      .1       0
  550.12     .06       0  693.27      .1       0
#XS Ineff= 2 , 0
                          343.14         1405.88
Permanent Ineff=
       F       F
Bank Sta=302.1,328.7
XS Rating Curve= 0 ,0
Exp/Cntr=0.3,0.1

Type RM Length L Ch R = 1 ,12611   ,452.1,450,447
XS GIS Cut Line= 3
 2474457.1532774665302.617518267     2474702.894      665462.368
     2475042.959      665691.417
#Sta/Elev= 30
       0 1544.49    59.1 1510.38   130.7    1471     145 1463.73   198.7 1440.21
   230.9 1421.22   254.8  1410.9   270.2 1401.06   283.4 1395.04   292.9 1393.32
   304.9 1393.77   310.7 1395.36     317 1397.04   344.2 1396.27     394 1398.53
   431.7 1397.94   460.5 1401.75   471.4 1405.88   518.1 1429.49   538.9 1438.48
   558.5 1450.03   582.3 1451.26   591.9 1457.77   610.4 1466.46   635.3 1484.97
   659.4 1494.83   685.3 1496.01   688.4 1497.31     698 1504.77   703.1 1507.63
#Mann= 6 ,-1 , 0
       0      .1       0   283.4    .045       0   310.7      .1       0
  326.31      .1       0  468.22     .06       0  611.81      .1       0
#XS Ineff= 2 , 0
                          392.96         1406.31
Permanent Ineff=
       F       F
Bank Sta=283.4,310.7
XS Rating Curve= 0 ,0
Exp/Cntr=0.3,0.1

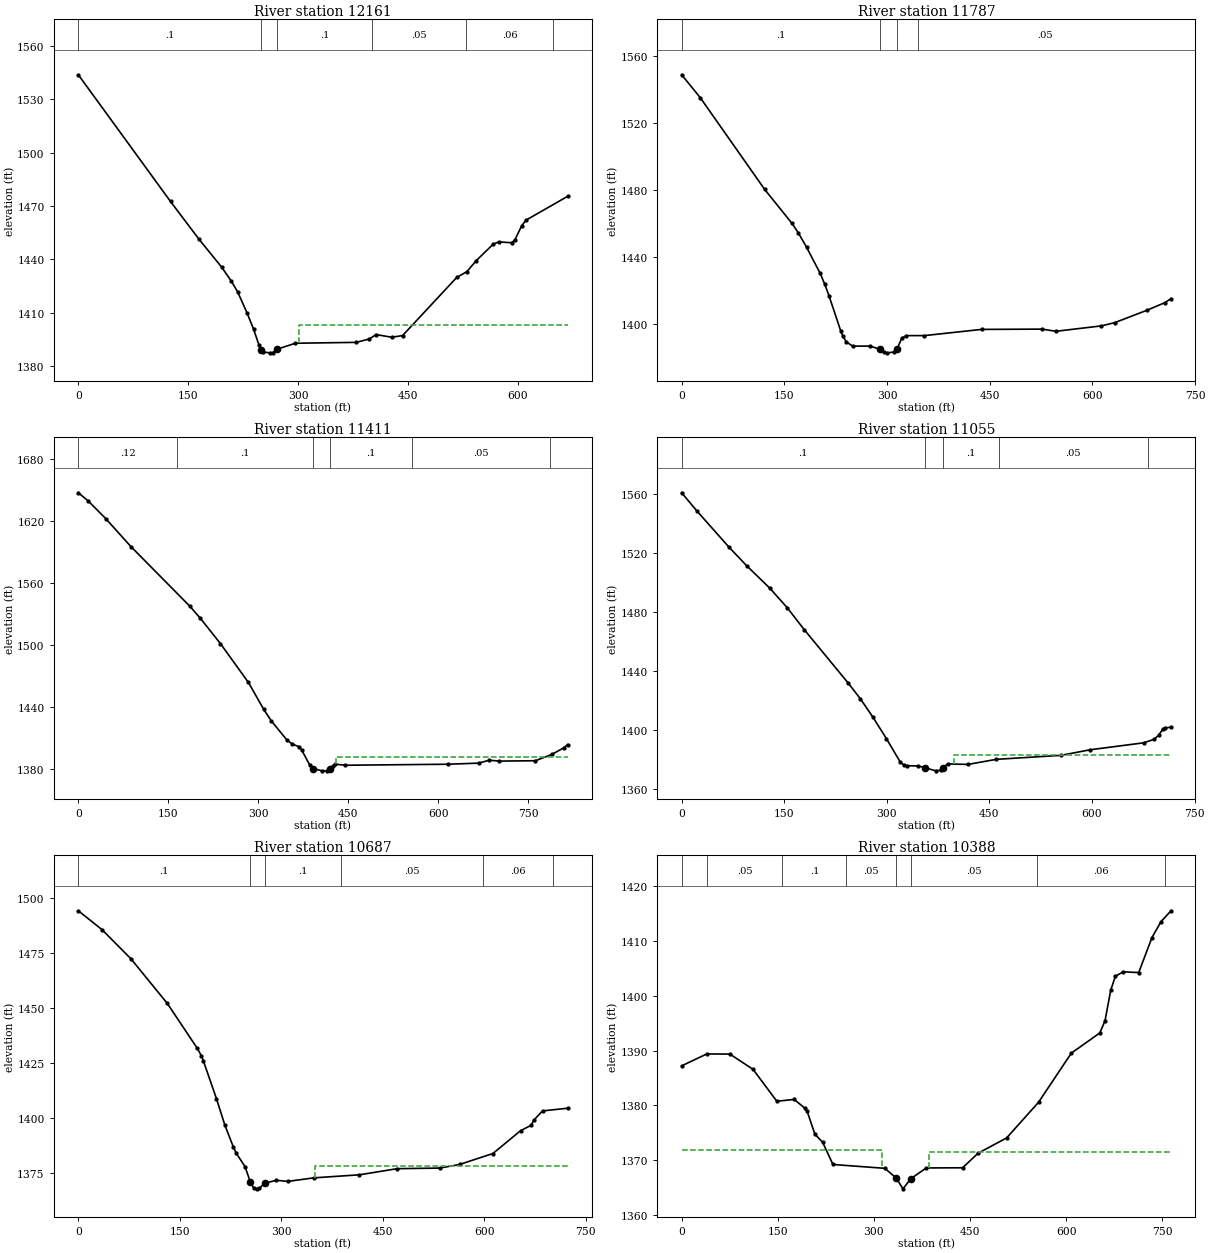
Type RM Length L Ch R = 1 ,12161   ,365.1,373.4,381.5
XS GIS Cut Line= 3
2474223.38415946665733.225944762     2474460.861      665837.082
     2474832.308      666008.535
#Sta/Elev= 30
       0 1543.62   125.9 1472.51   164.8 1451.34   195.8 1435.65   208.9 1427.84
   217.6 1421.78   230.7  1409.7   239.4 1400.83   246.8 1391.83   249.8 1389.31
   252.5 1388.08   261.3 1387.57   265.7 1387.73     271 1389.55   296.5 1392.96
   379.5 1393.45   397.1  1395.3   406.7 1397.81   427.8 1396.35   442.8 1397.24
   516.8 1429.89   530.8 1433.17   543.2 1439.22   566.4 1448.48   574.1 1449.83
   591.7 1449.37   596.1 1450.86   605.6 1458.95   611.6 1462.08   668.3 1475.41
#Mann= 6 ,-1 , 0
       0      .1       0   249.8    .045       0     271      .1       0
  400.92     .05       0  529.08     .06       0  648.86      .1       0
#XS Ineff= 2 , 0
                          301.11         1403.44
Permanent Ineff=
       F       F
Bank Sta=249.8,271
XS Rating Curve= 0 ,0
Exp/Cntr=0.3,0.1

Type RM Length L Ch R = 1 ,11787   ,385.8,376.6,365.2
XS GIS Cut Line= 2
2474040.60901224665871.248971338     2474472.235      666440.996
#Sta/Elev= 30
       0 1548.77      27 1535.19   121.2 1480.31   161.2 1459.96   170.2 1454.47
   182.4 1445.78   202.3 1430.15   208.9 1423.78   215.5  1416.4   232.5 1395.57
   235.4 1392.64   240.4 1389.22   249.7 1386.68   275.6 1386.68   289.6 1384.74
   295.6 1382.86   300.6 1382.65   309.6 1383.13   314.9 1385.21   321.5  1391.4
   328.1 1392.94   354.6 1392.95   438.1 1396.65   526.6 1396.82   546.7 1395.52
     613 1398.75   632.8 1400.72   679.2 1408.01   705.7  1412.6   714.8    1415
#Mann= 4 ,-1 , 0
       0      .1       0   289.6    .045       0   314.9      .1       0
  345.61     .05       0
Bank Sta=289.6,314.9
XS Rating Curve= 0 ,0
Exp/Cntr=0.3,0.1

Type RM Length L Ch R = 1 ,11411   ,353.8,355.5,353.9
XS GIS Cut Line= 3
2473659.49858077666257.909838458     2474042.341      666394.449
      2474424.98      666540.326
#Sta/Elev= 30
       0 1647.44    16.2 1639.69    45.9 1622.28    87.8 1595.21   186.1 1537.35
   203.7 1525.59     237 1501.19   283.7 1463.49   309.2 1437.38     322 1426.09
   347.6 1407.89   355.9 1404.09   368.7 1400.95   372.9 1397.61   385.7 1383.62
   391.5 1380.03   406.4 1377.81   415.5 1377.97   419.7 1379.31     424 1382.59
   428.3 1384.28   445.4 1383.25   616.7 1384.22   667.5 1385.28   685.1  1388.1
   702.3 1387.26   762.2 1387.61   789.5 1393.69   809.3 1400.06     816 1403.27
#Mann= 6 ,-1 , 0
       0     .12       0   164.1      .1       0   391.5    .045       0
   419.7      .1       0  556.94     .05       0  786.48     .06       0
#XS Ineff= 2 , 0
                          429.35         1391.24
Permanent Ineff=
       F       F
Bank Sta=391.5,419.7
XS Rating Curve= 0 ,0
Exp/Cntr=0.3,0.1

Type RM Length L Ch R = 1 ,11055   ,363.2,368.2,365.7
XS GIS Cut Line= 2
2473597.56212147666606.0711864492474269.81354237666851.122498122
#Sta/Elev= 30
       0  1560.5    22.5 1548.08    69.4 1523.62    94.9 1511.25     129 1495.94
   154.2 1482.85   179.4 1467.86   243.9 1431.62     261  1421.4   279.3 1409.03
   299.3 1394.33   319.8 1378.28   324.8 1376.51   329.1 1375.95   346.1 1375.79
   355.7 1374.59   371.7 1372.49   379.1 1373.01   382.5 1374.63   388.7 1377.19
   418.5 1376.82   460.2 1380.27   554.7 1382.96   597.5 1386.76   675.5 1391.43
   691.1 1393.86   697.4 1396.62   703.7  1400.7   706.7 1401.55   715.5 1401.99
#Mann= 5 ,-1 , 0
       0      .1       0   355.7    .045       0   382.5      .1       0
  463.55     .05       0  681.49     .06       0
#XS Ineff= 2 , 0
                          397.78         1383.22
Permanent Ineff=
       F       F
Bank Sta=355.7,382.5
XS Rating Curve= 0 ,0
Exp/Cntr=0.3,0.1

Type RM Length L Ch R = 1 ,10687   ,305.9,299.7,291.1
XS GIS Cut Line= 2
2473425.70190678666880.6818182862474109.96403437 667116.12395951
#Sta/Elev= 30
       0 1494.39    34.9 1485.82    78.1 1472.38   131.6 1452.12   175.7 1431.75
     182 1428.24   185.1 1425.77   204.2 1408.74   216.8 1396.53   229.2 1386.68
   233.8 1383.68   246.5 1377.69   254.3 1370.72   259.1 1368.05   263.8 1367.55
   267.6 1367.73   275.4 1370.13     293 1371.44   309.9 1370.95     348 1372.56
   415.7 1373.95   471.5 1376.75   534.4 1377.02   563.7 1378.66   613.1 1383.67
     654 1394.09   669.5 1396.51   673.7 1398.93   686.4 1403.09   723.6 1404.33
#Mann= 6 ,-1 , 0
       0      .1       0   254.3    .045       0   275.4      .1       0
  388.85     .05       0  597.88     .06       0  701.31    .055       0
#XS Ineff= 2 , 0
                          349.95         1377.85
Permanent Ineff=
       F       F
Bank Sta=254.3,275.4
XS Rating Curve= 0 ,0
Exp/Cntr=0.3,0.1

Type RM Length L Ch R = 1 ,10388   ,88.3,94.5,97.3
XS GIS Cut Line= 3
2473355.79125518667263.0465607352473536.89313747667278.715666204
     2474112.601      667194.064
#Sta/Elev= 30
       0  1387.2    39.1 1389.37    75.2 1389.35   111.4 1386.56   148.5 1380.73
   175.6 1381.06   191.7 1379.51   195.8 1378.91   207.9 1374.71     220 1373.24
   236.1 1369.17   317.1 1368.47   334.8 1366.69   345.4 1364.72   357.5 1366.56
   381.8 1368.54   438.4 1368.57   462.6 1371.23   507.1 1374.02   556.9 1380.53
   608.2 1389.53   652.6 1393.21   660.7 1395.44   669.7 1401.06   676.9 1403.58
     689 1404.38   713.3 1404.25     734 1410.65   748.2 1413.58   763.7 1415.54
#Mann= 8 ,-1 , 0
       0      .1       0   39.54     .05       0  157.17      .1       0
  257.24     .05       0   334.8    .045       0   357.5     .05       0
  555.22     .06       0  753.87      .1       0
#XS Ineff= 2 , 0
          313.31 1371.75  385.95         1371.37
Permanent Ineff=
       F       F
Bank Sta=334.8,357.5
XS Rating Curve= 0 ,0
Exp/Cntr=0.5,0.3