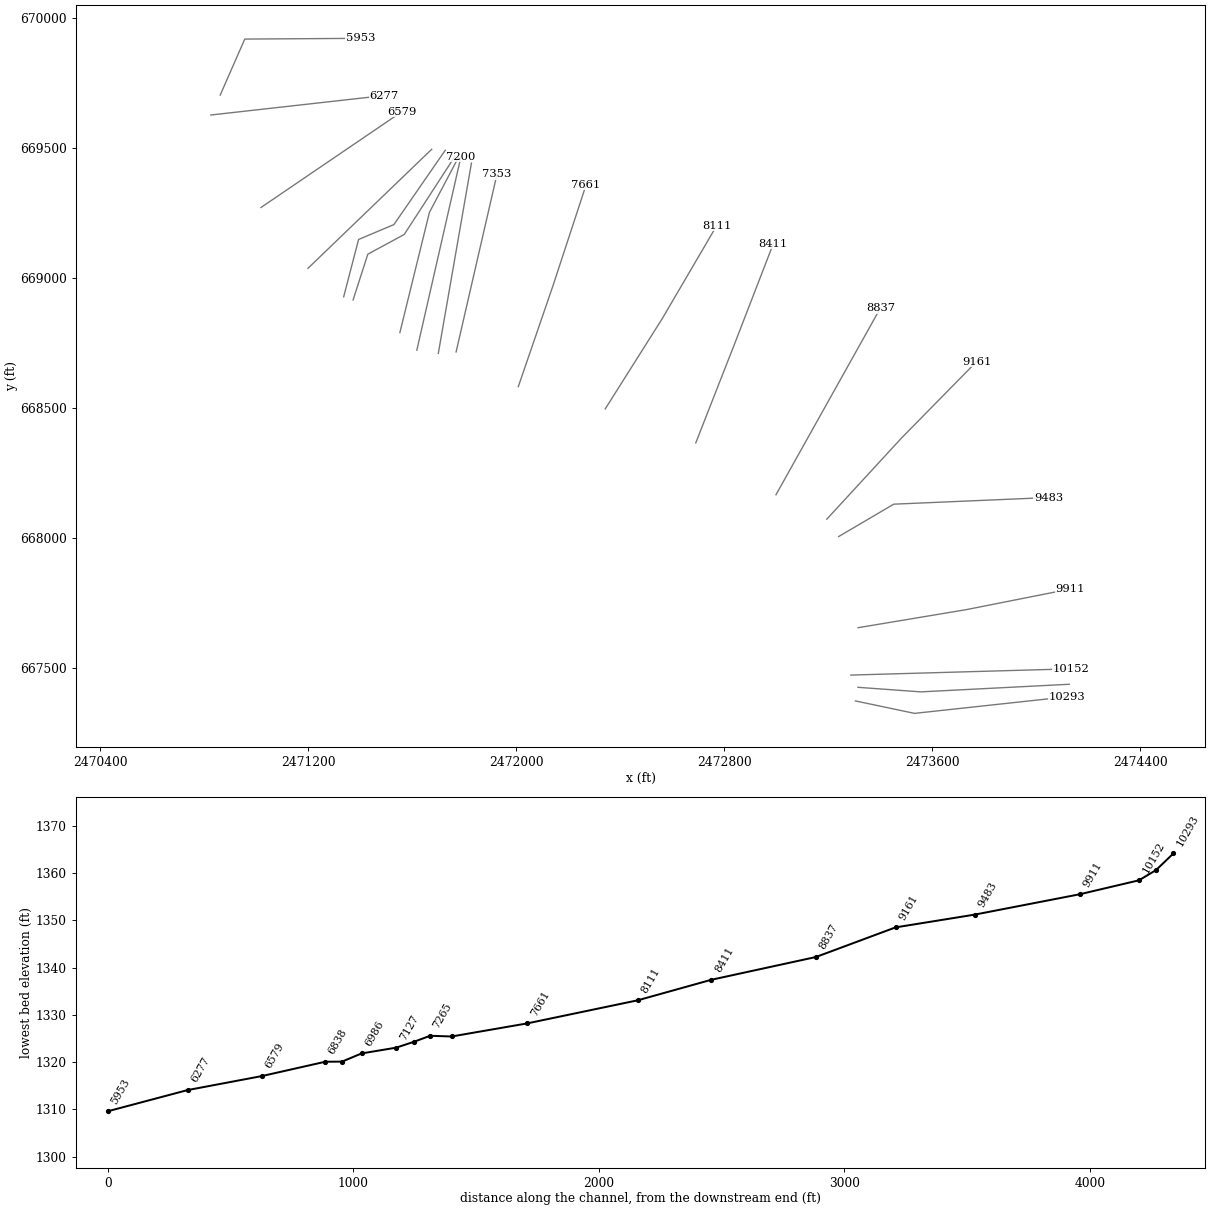
HEC-RAS study BRUSHRN1.prj: BRUSHRN1

--- BRUSHRN1.g01 (geometry) --- (continued)

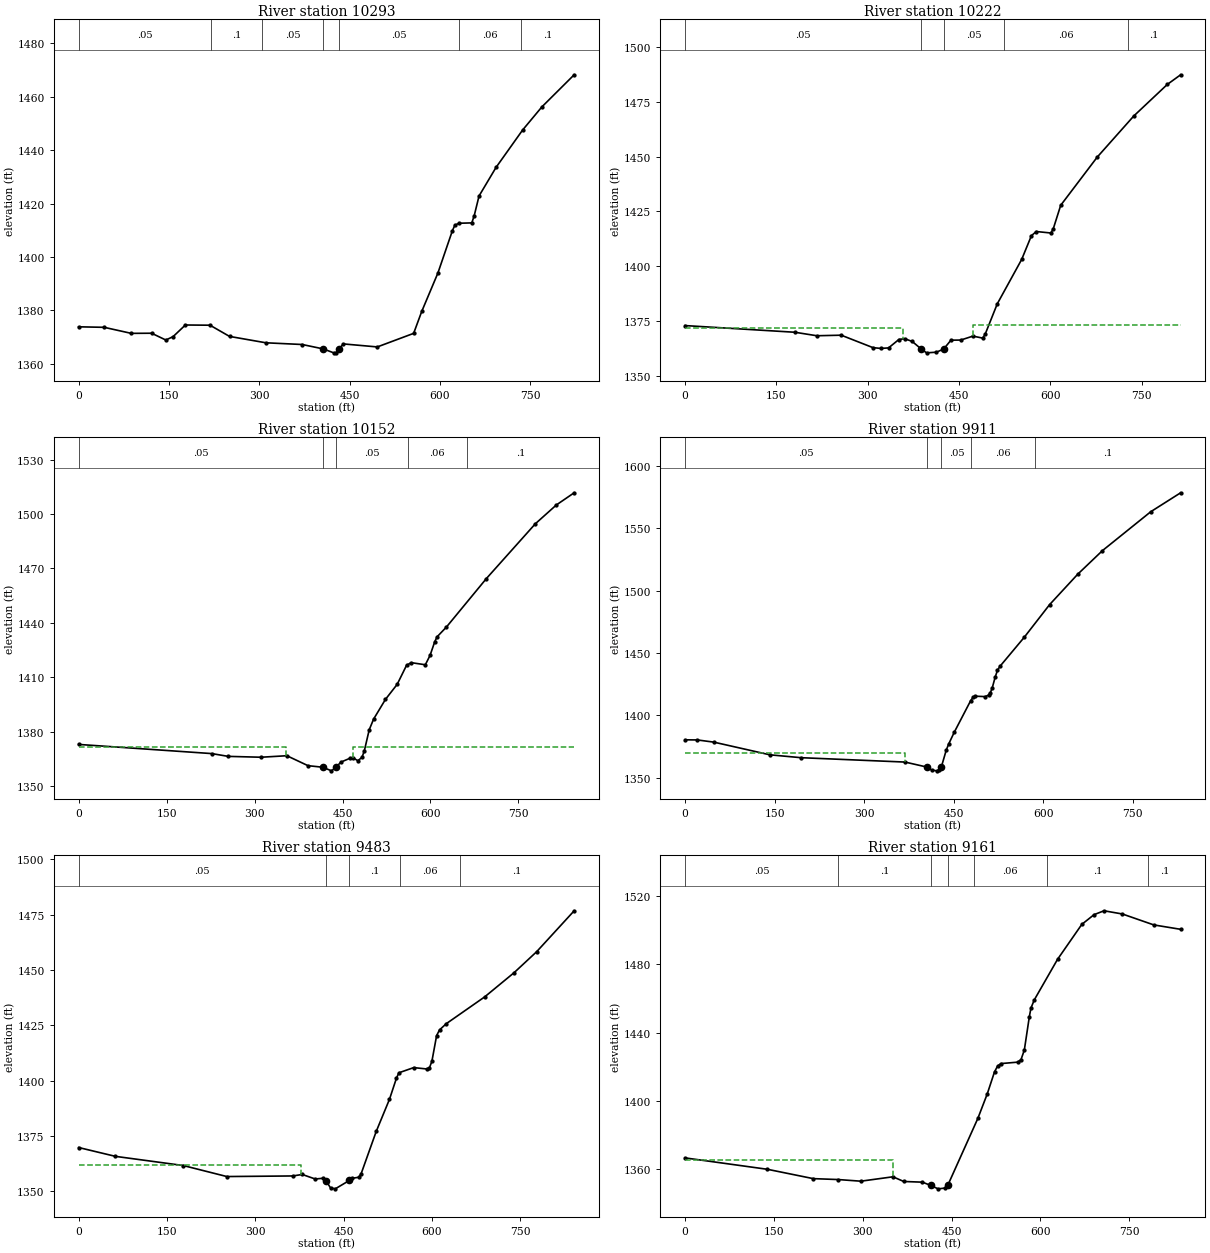
Type RM Length L Ch R = 1 ,10293   ,72.1,71.3,70.9
XS GIS Cut Line= 3
2473305.25801528667372.9943842552473532.49938665667325.047413231
2474119.80832612667388.859989515
#Sta/Elev= 30
       0 1373.86    42.4 1373.67    87.4 1371.41   121.2 1371.46   144.8 1368.92
   156.9 1370.19   177.3 1374.54   218.2 1374.46   250.6 1370.27     311 1367.88
   371.3 1367.24   406.5 1365.58   423.6 1364.12   427.6  1364.2   431.9 1365.43
   439.7 1367.46     496 1366.33   556.4 1371.41   569.8  1379.6   596.6 1393.94
   620.8 1409.87   624.8 1411.86   631.5 1412.62     653 1412.75     657 1415.46
     665 1422.82   693.2  1433.5   737.4 1447.51   769.4 1456.17     823 1468.18
#Mann= 7 ,-1 , 0
       0     .05       0  220.12      .1       0  303.85     .05       0
   406.5    .045       0   431.9     .05       0  631.76     .06       0
  734.78      .1       0
#XS Ineff= 2 , 0
          380.94 1366.13  443.99         1365.95
Permanent Ineff=
       F       F
Bank Sta=406.5,431.9
XS Rating Curve= 0 ,0
Exp/Cntr=0.5,0.3

Type RM Length L Ch R = 1 ,10222   ,69.5,69.4,69.3
XS GIS Cut Line= 3
2473314.91457758 667425.367287952473557.03901323667407.801625365
2474127.56813178667437.079341102
#Sta/Elev= 30
       0    1373   180.3 1369.96   216.4 1368.37   256.5 1368.62   308.6 1362.95
   321.5 1362.59   334.2 1362.83   351.1 1366.65   360.6 1367.04   373.1 1365.76
   388.3 1362.23   396.7 1360.58   412.7 1360.87   424.7  1362.3   436.7 1366.35
   452.7  1366.4   472.8  1368.2   488.8  1367.3   492.8 1368.99   512.8 1382.91
   552.9 1403.15   568.9 1413.97   576.9 1415.86   600.9 1415.18   604.9 1417.21
     617 1427.81     677 1449.77   737.1 1468.52   792.1 1482.88     814 1487.28
#Mann= 5 ,-1 , 0
       0     .05       0   388.3    .045       0   424.7     .05       0
  523.91     .06       0  727.09      .1       0
#XS Ineff= 2 , 0
          358.06 1372.05   473.2         1373.19
Permanent Ineff=
       F       F
Bank Sta=388.3,424.7
XS Rating Curve= 0 ,0
Exp/Cntr=0.5,0.3

Type RM Length L Ch R = 1 ,10152   ,238.1,241.5,243.7
XS GIS Cut Line= 2
2473287.78782161667472.478394906     2474132.498      667496.438
#Sta/Elev= 30
       0 1372.99     227 1367.94   255.1  1366.4   311.1 1365.93   355.1 1366.76
   391.1 1361.28   416.5 1360.41   431.1 1358.43   439.1 1360.48   447.1 1363.22
   463.1 1365.42   467.1 1365.78   476.1 1364.02   483.2 1365.86   487.2 1369.49
   495.5 1381.06     503 1386.95   523.2 1397.82   543.2 1406.11   559.2 1416.62
   567.2 1418.06   591.2  1416.9   599.2 1422.03   607.2 1429.55   611.2  1432.3
   627.2  1437.7   695.2 1464.38   778.9 1494.65   814.6 1504.98     845  1511.7
#Mann= 5 ,-1 , 0
       0     .05       0   416.5    .045       0   439.1     .05       0
  560.98     .06       0   662.1      .1       0
#XS Ineff= 2 , 0
          353.71 1371.52  467.99         1371.36
Permanent Ineff=
       F       F
Bank Sta=416.5,439.1
XS Rating Curve= 0 ,0
Exp/Cntr=0.3,0.1

Type RM Length L Ch R = 1 ,9911    ,428.5,427.4,421.1
XS GIS Cut Line= 3
2473315.36604817667654.777132477      2473730.32      667724.032
     2474131.799      667803.668
#Sta/Elev= 30
       0 1380.38    20.4 1380.28      48 1378.53     142 1368.34     194 1366.04
   368.4 1362.52   404.9 1358.52     413 1356.16   421.1 1355.48   425.2 1356.03
   429.3 1358.72   437.4 1372.09   441.5 1377.01   450.7 1386.35   478.2  1411.7
   482.3 1414.43   486.4 1415.39   502.7 1415.05   508.6 1416.32   510.8 1417.65
   514.3  1421.8   519.3 1430.57   523.1 1436.06   527.2 1439.25   567.9 1462.58
   610.6 1488.92   657.6 1513.27   699.1 1532.25     780 1563.46     830 1578.65
#Mann= 5 ,-1 , 0
       0     .05       0   404.9    .045       0   429.3     .05       0
  479.49     .06       0  585.47      .1       0
#XS Ineff= 2 , 0
          368.12 1369.76
Permanent Ineff=
       F       F
Bank Sta=404.9,429.3
XS Rating Curve= 0 ,0
Exp/Cntr=0.3,0.1

Type RM Length L Ch R = 1 ,9483    ,307.1,322.6,342.8
XS GIS Cut Line= 3
     2473240.856      668005.5712473452.78039703668130.211228823
     2474048.307      668155.793
#Sta/Elev= 30
       0 1369.84    62.5 1365.85   177.7 1361.71   251.8 1356.73   363.9    1357
   379.9 1357.67     402 1355.62     416 1355.98     420 1354.93     428 1351.59
     436 1351.18     460 1354.98     464  1355.9     476 1356.42     480 1358.03
   505.6 1377.11   528.1 1391.61     540 1401.18   544.1 1403.59   569.3 1405.93
   592.1 1405.29   596.1  1405.9   600.2  1408.8   608.2 1420.39   613.1 1422.93
   624.6 1425.76   689.9 1437.87   739.8 1448.79   778.2 1458.28   841.9 1476.75
#Mann= 5 ,-1 , 0
       0     .05       0     420    .045       0     460      .1       0
  546.83     .06       0  648.24      .1       0
#XS Ineff= 2 , 0
          378.46 1362.05
Permanent Ineff=
       F       F
Bank Sta=420,460
XS Rating Curve= 0 ,0
Exp/Cntr=0.3,0.1

Type RM Length L Ch R = 1 ,9161    ,319.6,324.2,329.3
XS GIS Cut Line= 3
     2473195.242      668072.521     2473484.337      668386.627
     2473771.676      668679.222
#Sta/Elev= 30
       0 1366.61   139.1 1359.93   216.5 1354.46   258.7 1353.92   296.8 1352.96
   351.1 1355.54   369.3 1352.79   400.9 1352.39   414.6 1350.52   427.3 1348.48
   438.5 1348.91   444.1 1350.86   494.5 1389.77   510.3 1404.05   522.6    1417
   527.8 1420.41   533.4 1421.87   561.8 1422.72   567.4 1424.22     573 1429.83
   581.5 1449.45   584.2 1454.43   589.8  1459.2   629.1 1482.97   670.1 1503.45
   690.8 1509.15   707.6 1511.41   738.6 1509.53   791.7 1503.12     837 1500.55
#Mann= 7 ,-1 , 0
       0     .05       0   258.7      .1       0   414.6    .045       0
   444.1      .1       0  488.28     .06       0  610.46      .1       0
  782.45      .1       0
#XS Ineff= 2 , 0
          351.62 1365.31
Permanent Ineff=
       F       F
Bank Sta=414.6,444.1
XS Rating Curve= 0 ,0
Exp/Cntr=0.3,0.1

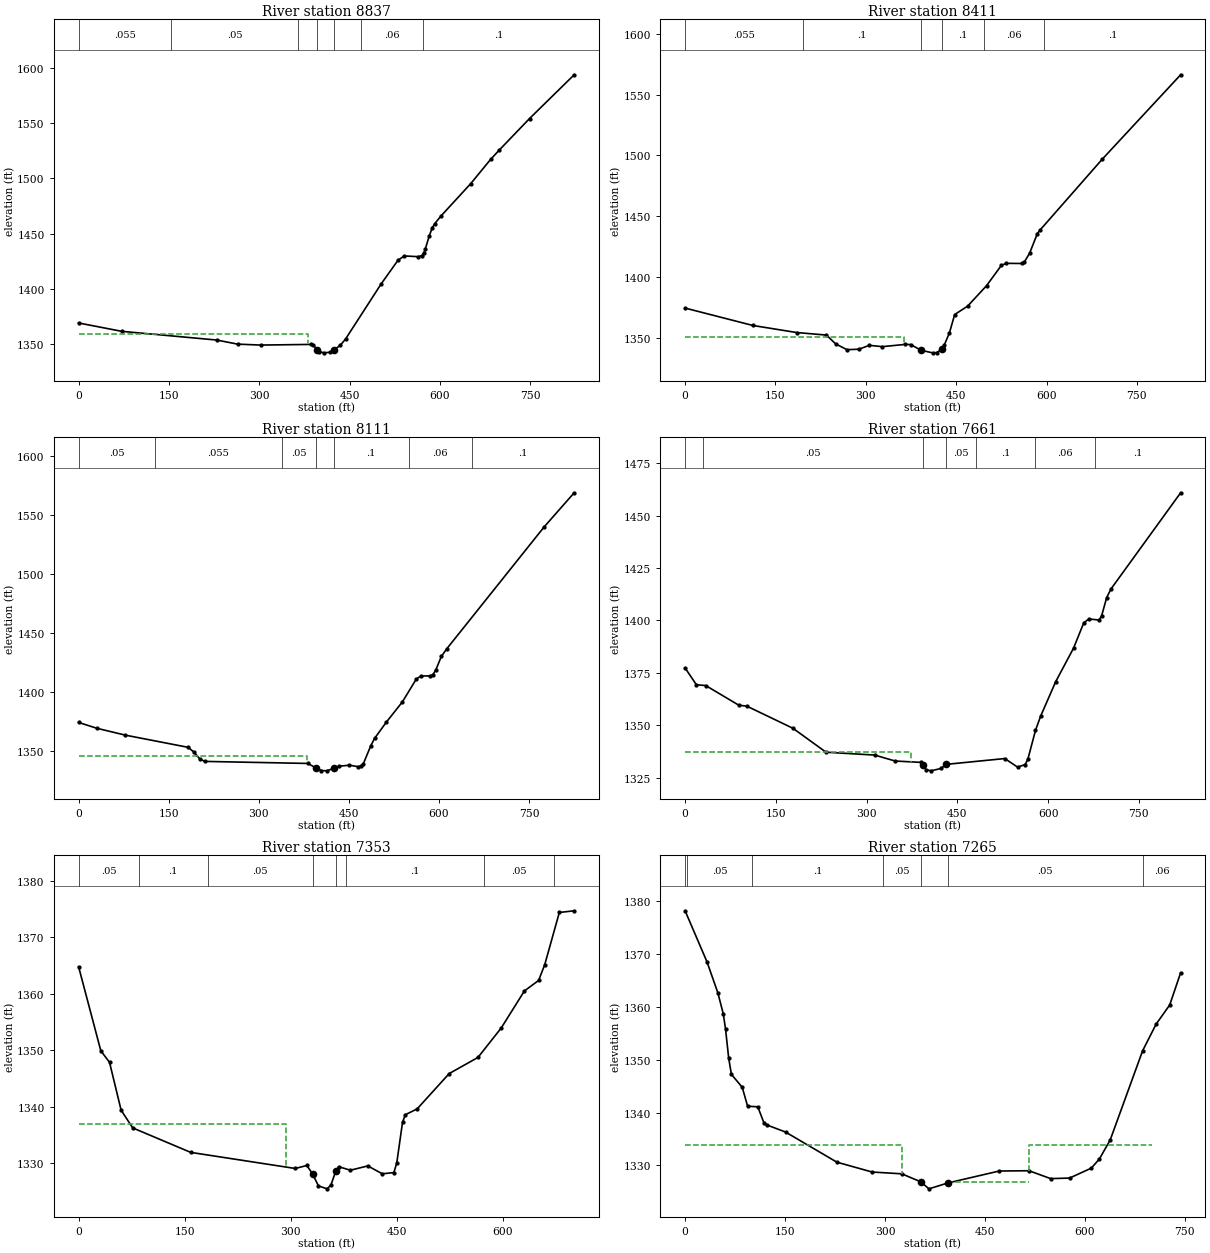
Type RM Length L Ch R = 1 ,8837    ,421,425.8,427.6
XS GIS Cut Line= 2
     2472999.828      668166.556     2473401.391      668885.027
#Sta/Elev= 30
       0 1369.24    71.6 1361.68   229.5 1353.79     264  1350.1   302.2 1349.25
   385.3 1349.83   389.9    1349   396.3 1345.07   399.5 1343.27     408 1342.22
   417.4 1342.74   424.1 1344.87   434.5 1348.96   443.3 1354.65   502.3 1404.43
   530.7 1426.16   541.1 1429.87     564 1429.23   569.7 1430.03   573.2 1432.39
   575.6 1435.75   582.3 1447.85   587.3 1455.19   591.5 1459.11     602  1466.1
   651.1  1495.2   684.3 1517.21     699 1525.85     749  1554.2   823.1 1593.78
#Mann= 7 ,-1 , 0
       0    .055       0  153.48     .05       0   364.5      .1       0
   396.3    .045       0   424.1      .1       0  468.54     .06       0
  572.59      .1       0
#XS Ineff= 2 , 0
          380.47 1359.22
Permanent Ineff=
       F       F
Bank Sta=396.3,424.1
XS Rating Curve= 0 ,0
Exp/Cntr=0.3,0.1

Type RM Length L Ch R = 1 ,8411    ,302.9,300,297.1
XS GIS Cut Line= 3
     2472691.302       668366.16     2472842.259      668751.525
     2472989.545      669132.787
#Sta/Elev= 30
       0 1374.28   112.5 1359.95   185.3 1354.13   234.7 1352.03   249.9 1344.79
   268.7 1340.01   288.6  1340.4   305.7 1343.59   327.5  1342.5   364.4 1344.32
   374.5 1344.24   391.7 1339.52   410.7 1337.41   417.5  1337.6   426.1 1340.39
   426.1 1340.44   430.3 1343.89   438.9 1354.01   447.5 1368.97   468.9 1375.83
   500.4 1392.71   525.1  1409.5   533.3 1411.12   558.7 1411.01   563.3 1412.34
   571.9 1419.49   584.7 1435.56     589 1438.43   692.1 1496.71   822.6 1566.45
#Mann= 6 ,-1 , 0
       0    .055       0  196.51      .1       0   391.7    .045       0
   426.1      .1       0  496.22     .06       0  596.04      .1       0
#XS Ineff= 2 , 0
          363.08 1350.52
Permanent Ineff=
       F       F
Bank Sta=391.7,426.1
XS Rating Curve= 0 ,0
Exp/Cntr=0.3,0.1

Type RM Length L Ch R = 1 ,8111    ,443.3,450,451.1
XS GIS Cut Line= 3
     2472343.018      668496.906     2472563.511      668846.271
     2472771.444      669201.748
#Sta/Elev= 30
       0 1374.06    30.7 1369.06      78 1363.28   182.1    1353   191.5 1349.17
   201.8  1343.1     210 1341.06   381.7 1339.33   395.6 1335.35   404.3 1333.35
     413 1333.07   424.7 1335.19   433.5 1336.98   450.9 1337.86   465.6 1336.57
   469.5 1337.04   474.1 1339.17   486.1 1353.97   492.6 1360.48   512.4 1374.37
     539 1391.46   562.1 1410.75   570.1 1413.42   585.5 1413.48   589.9 1414.59
   594.6 1418.42   603.8 1429.92   613.1 1436.56   775.3 1539.82     825 1568.55
#Mann= 7 ,-1 , 0
       0     .05       0  126.48    .055       0  339.09     .05       0
   395.6    .045       0   424.7      .1       0  549.78     .06       0
  654.61      .1       0
#XS Ineff= 2 , 0
          380.94 1345.83
Permanent Ineff=
       F       F
Bank Sta=395.6,424.7
XS Rating Curve= 0 ,0
Exp/Cntr=0.3,0.1

Type RM Length L Ch R = 1 ,7661    ,305,308.3,309.4
XS GIS Cut Line= 3
     2472008.679      668582.579     2472141.699      668969.903
     2472269.363      669359.006
#Sta/Elev= 30
       0 1377.33    18.7  1369.3    34.2 1368.92    89.1 1359.48   101.8 1359.13
   178.2 1348.52   232.9 1337.09   313.3 1335.72   347.1 1332.88   389.4 1332.24
   393.7 1331.14   397.9 1328.78   406.3 1328.19   423.2 1329.34   431.6 1331.29
   528.4 1334.06   549.5 1329.96   562.1 1331.19   566.5 1333.75   579.1 1347.48
   587.4 1354.17   612.6 1370.84   642.1 1386.84   658.9  1398.9   667.4 1400.72
   684.2 1400.22   688.4 1402.21   696.8 1410.97   703.9 1415.07     819    1461
#Mann= 7 ,-1 , 0
       0      .1       0   29.31     .05       0   393.7    .045       0
   431.6     .05       0  480.18      .1       0  579.02     .06       0
  677.87      .1       0
#XS Ineff= 2 , 0
           373.7 1337.13
Permanent Ineff=
       F       F
Bank Sta=393.7,431.6
XS Rating Curve= 0 ,0
Exp/Cntr=0.3,0.1

Type RM Length L Ch R = 1 ,7353    ,85.2,87.4,88.6
XS GIS Cut Line= 2
2471769.52136904668716.3174106932471926.60052735669399.393113367
#Sta/Elev= 30
       0 1364.77    31.4 1349.88    43.7 1347.85    60.1 1339.36    76.5 1336.22
   158.6 1331.88   306.4 1329.03   322.8 1329.56     331 1328.04   339.2 1325.94
   351.5 1325.42   356.9 1326.12   363.8 1328.59   367.9 1329.35   384.3 1328.72
     409 1329.48   429.5 1328.09   445.9  1328.3     450 1330.04   458.2 1337.28
   462.3 1338.57   478.8 1339.59   524.1 1345.85   564.9 1348.72   597.8 1353.95
   630.5  1360.5   650.6 1362.36   659.3 1365.17   679.9 1374.41   700.9 1374.71
#Mann= 8 ,-1 , 0
       0     .05       0   85.01      .1       0   182.8     .05       0
     331    .045       0   363.8     .05       0  378.39      .1       0
  573.97     .05       0  671.76     .06       0
#XS Ineff= 2 , 0
          292.89 1336.86
Permanent Ineff=
       F       F
Bank Sta=331,363.8
XS Rating Curve= 0 ,0
Exp/Cntr(USF)=0,0
Exp/Cntr=0.5,0.3

Type RM Length L Ch R = 1 ,7265    ,66.3,64.8,62.7
XS GIS Cut Line= 2
2471701.03067443668710.4525864822471828.45724038669443.032277327
#Sta/Elev= 30
       0 1378.14    32.9 1368.47    49.2 1362.61    57.3 1358.65    60.7 1355.78
    65.4 1350.28    69.5 1347.21    85.7 1344.78    93.8 1341.19   109.1 1341.08
   118.2 1338.07   122.2 1337.67   150.7 1336.31   227.8 1330.61   280.6 1328.75
   325.2 1328.41   353.7 1326.89   365.9 1325.57   394.3 1326.68   471.4 1328.94
   516.1 1328.99   548.6  1327.5     577 1327.61   609.5 1329.48   621.6  1331.2
   637.9 1334.81   686.6 1351.69   706.9 1356.73   727.2 1360.33   743.6 1366.42
#Mann= 7 ,-1 , 0
       0      .1       0    3.56     .05       0  101.12      .1       0
  296.22     .05       0   353.7    .045       0   394.3     .05       0
  686.44     .06       0
#XS Ineff= 4 ,-1
       0   325.2  1333.8   325.2     353  1326.8     395     516  1326.8
     516     700  1333.8
Permanent Ineff=
       F       F       F       F
Bank Sta=353.7,394.3
XS Rating Curve= 0 ,0
Exp/Cntr(USF)=0,0
Exp/Cntr=0.5,0.3

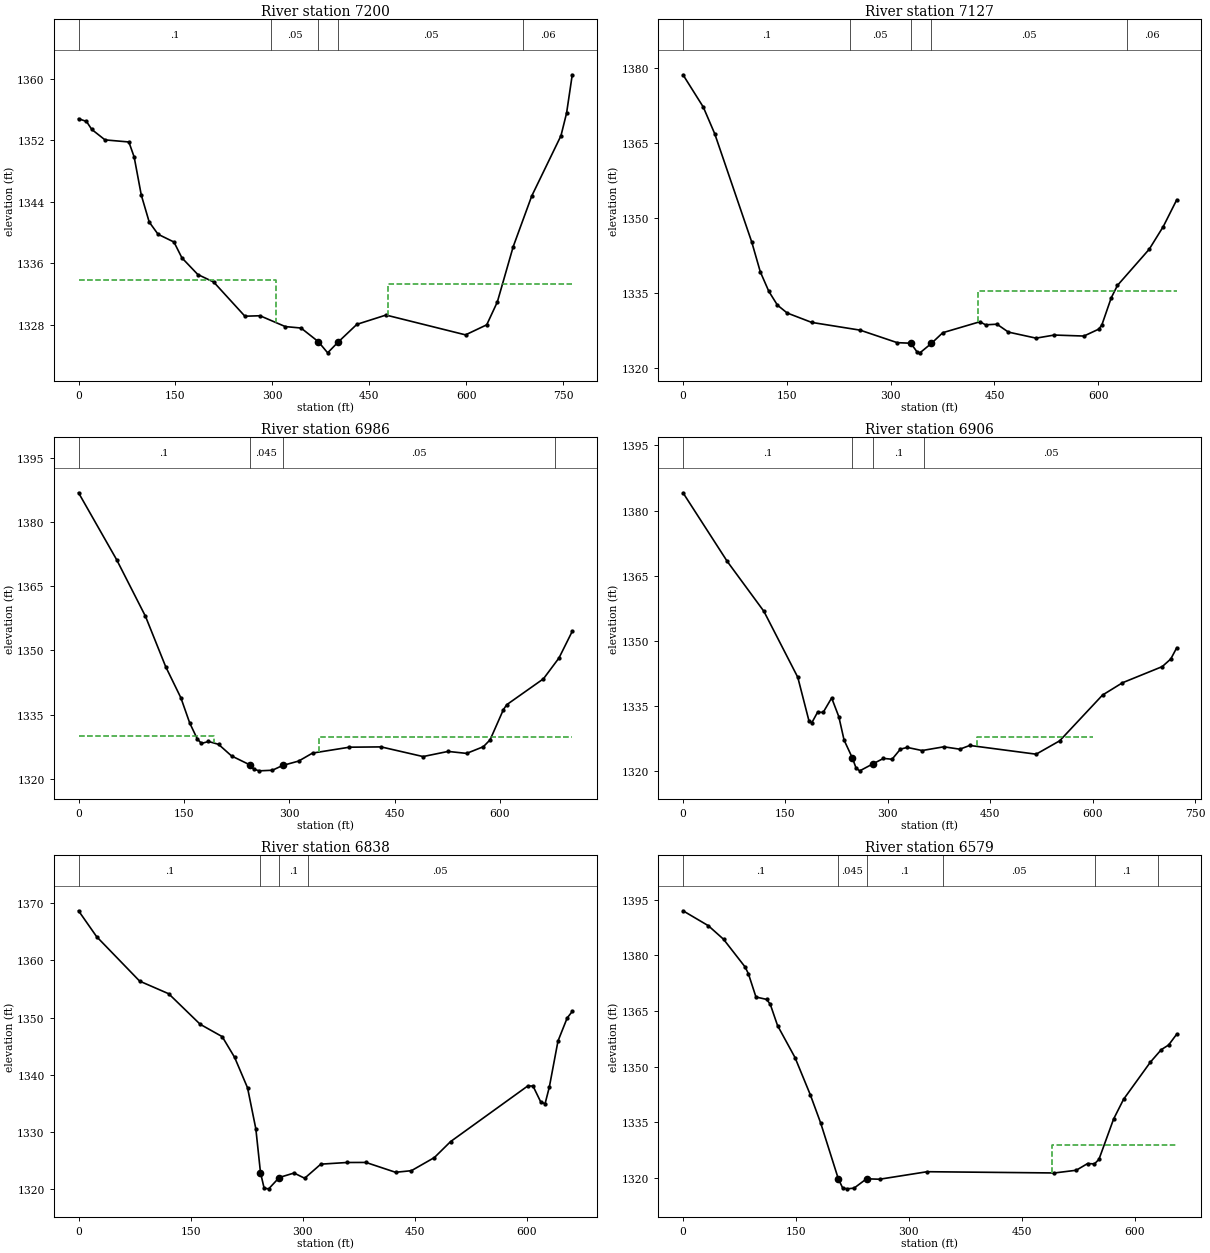
Type RM Length L Ch R = 1 ,7200    ,73.8,73.3,73
XS GIS Cut Line= 2
  2471618.442474668722.8976942172471788.20750717669467.989741825
#Sta/Elev= 30
       0 1354.81    12.3 1354.45    20.5 1353.41      41 1352.05    77.9 1351.78
    86.1 1349.82    97.1 1344.87   109.4 1341.35   123.1 1339.76   147.7 1338.75
     160 1336.69   184.6 1334.52   209.2 1333.54   257.5 1329.09   280.9 1329.15
     320 1327.74   344.4 1327.55   371.1 1325.78   385.6 1324.32   401.2 1325.67
   430.8 1328.03   475.9 1329.24     599 1326.66   631.8 1327.97   648.2 1330.94
   672.8 1338.15   701.5 1344.75   746.7 1352.59   755.4 1355.54   764.2 1360.53
#Mann= 5 ,-1 , 0
       0      .1       0  297.28     .05       0   371.1    .045       0
   401.2     .05       0  688.39     .06       0
#XS Ineff= 2 , 0
          306.23 1333.75  479.02         1333.29
Permanent Ineff=
       F       F
Bank Sta=371.1,401.2
XS Rating Curve= 0 ,0
Exp/Cntr=0.5,0.3

Type RM Length L Ch R = 1 ,7127    ,156.3,141,106.6
XS GIS Cut Line= 3
2471553.16161648668790.3971085792471666.88099522669253.265670554
2471777.25531727669462.575317528
#Sta/Elev= 30
       0  1378.7    29.3 1372.24    45.8 1366.91    99.4 1345.19   111.7 1339.26
     124 1335.36   136.4 1332.61   150.5 1331.03   185.9 1329.15   255.9  1327.6
   309.4  1325.1   329.1 1324.98   338.3 1323.21   342.3 1323.06   358.8 1324.94
   375.3 1327.09   428.9 1329.28   437.1 1328.67   453.6 1328.79   470.1 1327.21
   510.1    1326   536.4 1326.62   579.2 1326.42   600.6  1327.8   605.1 1328.63
   618.7 1334.08   627.7 1336.56   673.6  1343.8   693.9 1348.34   713.3 1353.68
#Mann= 5 ,-1 , 0
       0      .1       0  240.78     .05       0   329.1    .045       0
   358.8     .05       0  641.04     .06       0
#XS Ineff= 2 , 0
                          426.34         1335.52
Permanent Ineff=
       F       F
Bank Sta=329.1,358.8
XS Rating Curve= 0 ,0
Exp/Cntr(USF)=0,0
Exp/Cntr=0.5,0.3

Type RM Length L Ch R = 1 ,6986    ,78.5,79.9,90.5
XS GIS Cut Line= 4
2471373.25377876668916.2150081642471429.93062698669092.360067583
2471569.97653204  669168.2035678 2471765.0530698669469.108245406
#Sta/Elev= 30
       0 1386.88    54.2 1371.24    95.3 1357.98   124.1 1346.19   145.7 1338.92
   158.3 1333.02   169.1 1329.29     175 1328.24     185 1328.71   199.3 1328.04
   217.8 1325.33   243.6 1323.26   249.6  1322.2   257.6 1321.84     276 1321.98
   290.6  1323.1   313.3 1324.12   333.1 1325.99   385.6 1327.37   430.7 1327.44
   490.5 1325.18   526.1 1326.38   552.5 1325.92   576.3 1327.48   585.9 1329.09
   604.9 1336.17   609.7 1337.32   661.9 1343.37     684 1348.24   702.9 1354.48
#Mann= 4 ,-1 , 0
       0      .1       0   243.6    .045       0   290.6     .05       0
  678.23     .06       0
#XS Ineff= 2 , 0
          192.45    1330  342.05         1329.69
Permanent Ineff=
       F       F
Bank Sta=243.6,290.6
XS Rating Curve= 0 ,0
Exp/Cntr(USF)=0,0
Exp/Cntr=0.5,0.3

Type RM Length L Ch R = 1 ,6906    ,61.4,68.1,78.5
XS GIS Cut Line= 4
2471337.02757298668928.2191459592471394.41940673669149.036915808
2471530.23218619669206.3016981422471727.73820717669492.334642497
#Sta/Elev= 30
       0 1384.08    64.8 1368.29   118.5  1356.8   168.1 1341.63   184.6 1331.53
   188.7 1331.19   197.1  1333.6   205.3 1333.56   217.7 1336.88   228.2 1332.57
   235.9 1327.19   248.1 1323.05   253.5 1320.73   258.9 1320.11   277.8 1321.69
   293.6 1322.97   306.2 1322.78   318.4  1325.1   328.4  1325.5   350.1 1324.78
   382.1 1325.64   405.4 1325.09     420 1325.95   517.2 1323.94   551.7 1327.02
   614.4 1337.54   643.6 1340.37   701.9 1344.09   714.4 1345.85   723.1 1348.42
#Mann= 4 ,-1 , 0
       0      .1       0   248.1    .045       0   277.8      .1       0
  353.32     .05       0
#XS Ineff= 1 ,-1
     431     600    1328
Permanent Ineff=
       F
Bank Sta=248.1,277.8
XS Rating Curve= 0 ,0
Exp/Cntr=0.5,0.3

Type RM Length L Ch R = 1 ,6838    ,263,259.5,253.8
XS GIS Cut Line= 2
2471199.84839731669038.0816249182471675.67984453669496.170204615
#Sta/Elev= 30
       0 1368.64    24.2 1364.12    81.8 1356.35   120.6 1354.15   162.7 1348.82
   192.2 1346.66   208.8 1343.04   226.1 1337.72   237.2 1330.55   243.4 1322.93
   248.3 1320.18   254.4 1320.08   268.5 1322.06   288.3 1322.84   302.5 1321.93
   324.1 1324.39   359.1 1324.68   384.5 1324.69   424.1 1322.97   445.3 1323.25
     476 1325.54   497.7 1328.33     601 1338.05     608 1338.03   618.3 1335.26
   624.1 1334.93   629.8 1337.84   641.4 1345.89   653.7 1349.92   660.5 1351.06
#Mann= 4 ,-1 , 0
       0      .1       0   243.4    .045       0   268.5      .1       0
   307.1     .05       0
Bank Sta=243.4,268.5
XS Rating Curve= 0 ,0
Exp/Cntr(USF)=0,0
Exp/Cntr=0.3,0.1

Type RM Length L Ch R = 1 ,6579    ,308.6,301.5,289.7
XS GIS Cut Line= 2
2471018.93882204669272.0127876732471561.09587241669640.984607347
#Sta/Elev= 30
       0 1392.02    33.6    1388    53.8 1384.35    82.5 1376.86    86.9 1375.02
    96.9 1368.77   111.1 1368.12   115.9 1366.81   125.6 1361.06   148.8 1352.43
   169.1  1342.4   182.9 1334.77   206.3 1319.74   212.1 1317.26   217.9 1317.04
   227.2 1317.23   243.8 1319.75   261.1 1319.63   324.4 1321.66   493.3 1321.32
   522.3 1322.05   537.4 1323.86   546.5 1323.76   552.5    1325     572 1335.89
   585.2 1341.19   620.9 1351.23   635.3 1354.58     645 1355.82   655.8 1358.75
#Mann= 6 ,-1 , 0
       0      .1       0   206.3    .045       0   243.8      .1       0
  345.76     .05       0  546.92      .1       0  631.45     .06       0
#XS Ineff= 2 , 0
                          489.79         1328.73
Permanent Ineff=
       F       F
Bank Sta=206.3,243.8
XS Rating Curve= 0 ,0
Exp/Cntr=0.3,0.1

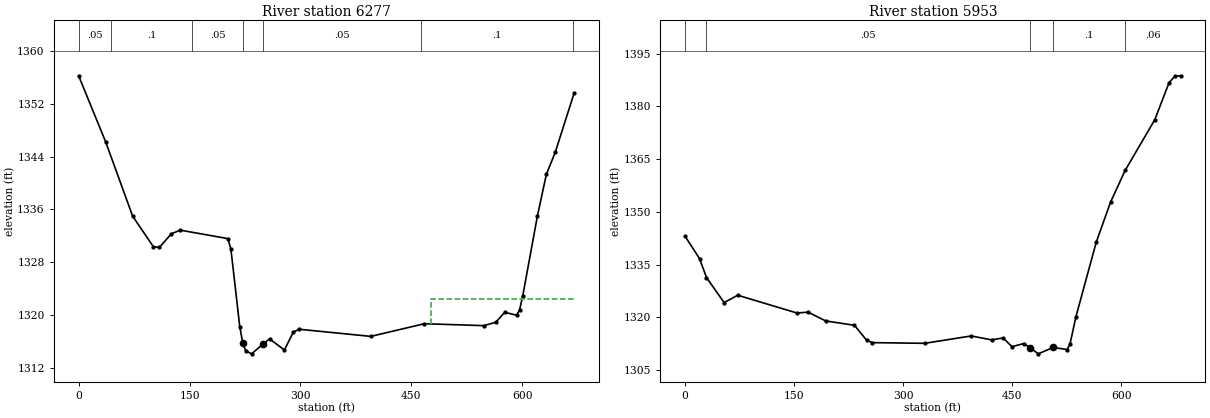
Type RM Length L Ch R = 1 ,6277    ,325.5,324.5,323.6
XS GIS Cut Line= 2
2470826.16439339669628.0472676982471492.05586629669702.794925143
#Sta/Elev= 30
       0 1356.29    36.8 1346.19      73 1334.99   101.2 1330.33   109.3 1330.25
   125.4 1332.31   137.4 1332.86   201.8 1331.58   205.9 1329.99   217.9  1318.2
     222 1315.71     226 1314.53     234 1314.09   249.2 1315.57   258.2 1316.36
   278.3 1314.67   290.4 1317.41   298.4 1317.82     395 1316.74   467.5 1318.66
     548 1318.37   564.1 1318.88   576.2  1320.4   592.3 1319.95   596.3 1320.78
   600.5 1322.85   620.5 1335.08   632.5 1341.33   644.6  1344.7   670.1 1353.69
#Mann= 7 ,-1 , 0
       0     .05       0   43.41      .1       0  153.43     .05       0
     222    .045       0   249.2     .05       0  462.79      .1       0
  669.03     .06       0
#XS Ineff= 2 , 0
                          476.07         1322.35
Permanent Ineff=
       F       F
Bank Sta=222,249.2
XS Rating Curve= 0 ,0
Exp/Cntr=0.3,0.1

Type RM Length L Ch R = 1 ,5953    ,221.1,235.4,254.6
XS GIS Cut Line= 3
2470862.18255698669704.6662429392470956.66879518669920.290850286
2471402.77400988669923.116111591
#Sta/Elev= 30
       0 1343.05    19.9 1336.69    29.4 1331.33    53.7 1324.19    72.3 1326.29
   153.9 1321.23   169.1 1321.48   193.4 1318.98   232.9 1317.74   249.5 1313.52
   257.5 1312.81   329.5 1312.61   393.5 1314.71   421.5 1313.59   437.5 1314.14
   449.5 1311.65   465.5 1312.54   474.6 1311.41   485.5 1309.62   506.4 1311.45
   525.5 1310.83   529.5 1312.54   537.5 1320.18   565.5 1341.42   585.1 1352.77
   605.2 1361.79     646 1376.23   665.5  1386.7   673.3 1388.56   681.5  1388.7
#Mann= 5 ,-1 , 0
       0      .1       0    29.4     .05       0   474.6    .045       0
   506.4      .1       0   605.2     .06       0
Bank Sta=474.6,506.4
XS Rating Curve= 0 ,0
Exp/Cntr=0.3,0.1