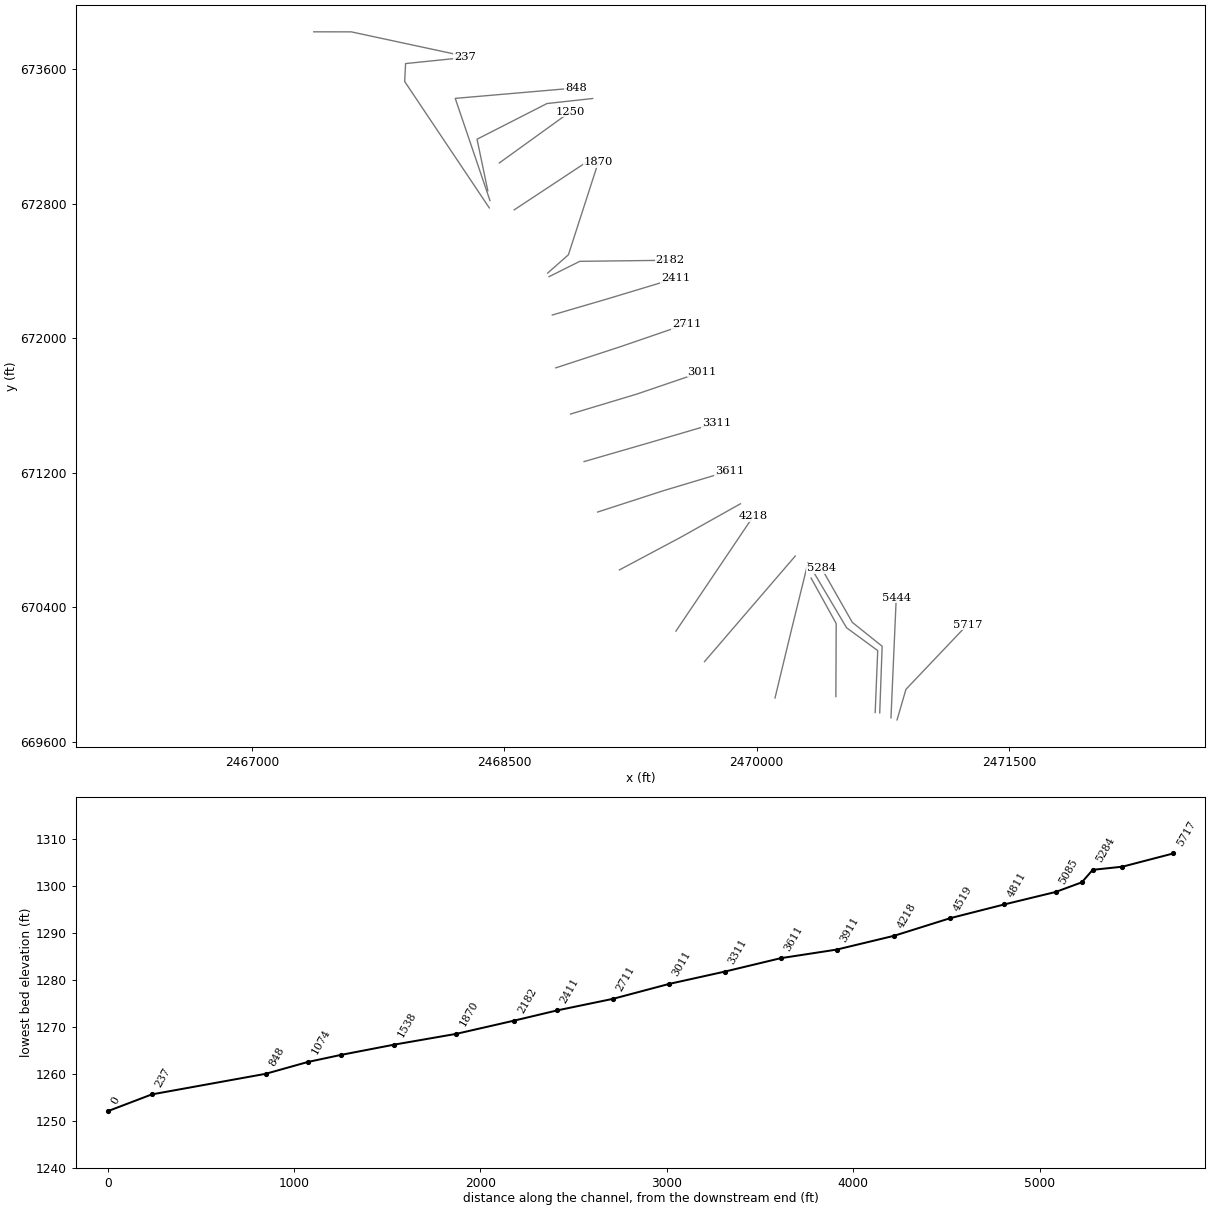
HEC-RAS study BRUSHRN1.prj: BRUSHRN1

--- BRUSHRN1.g01 (geometry) --- (continued)

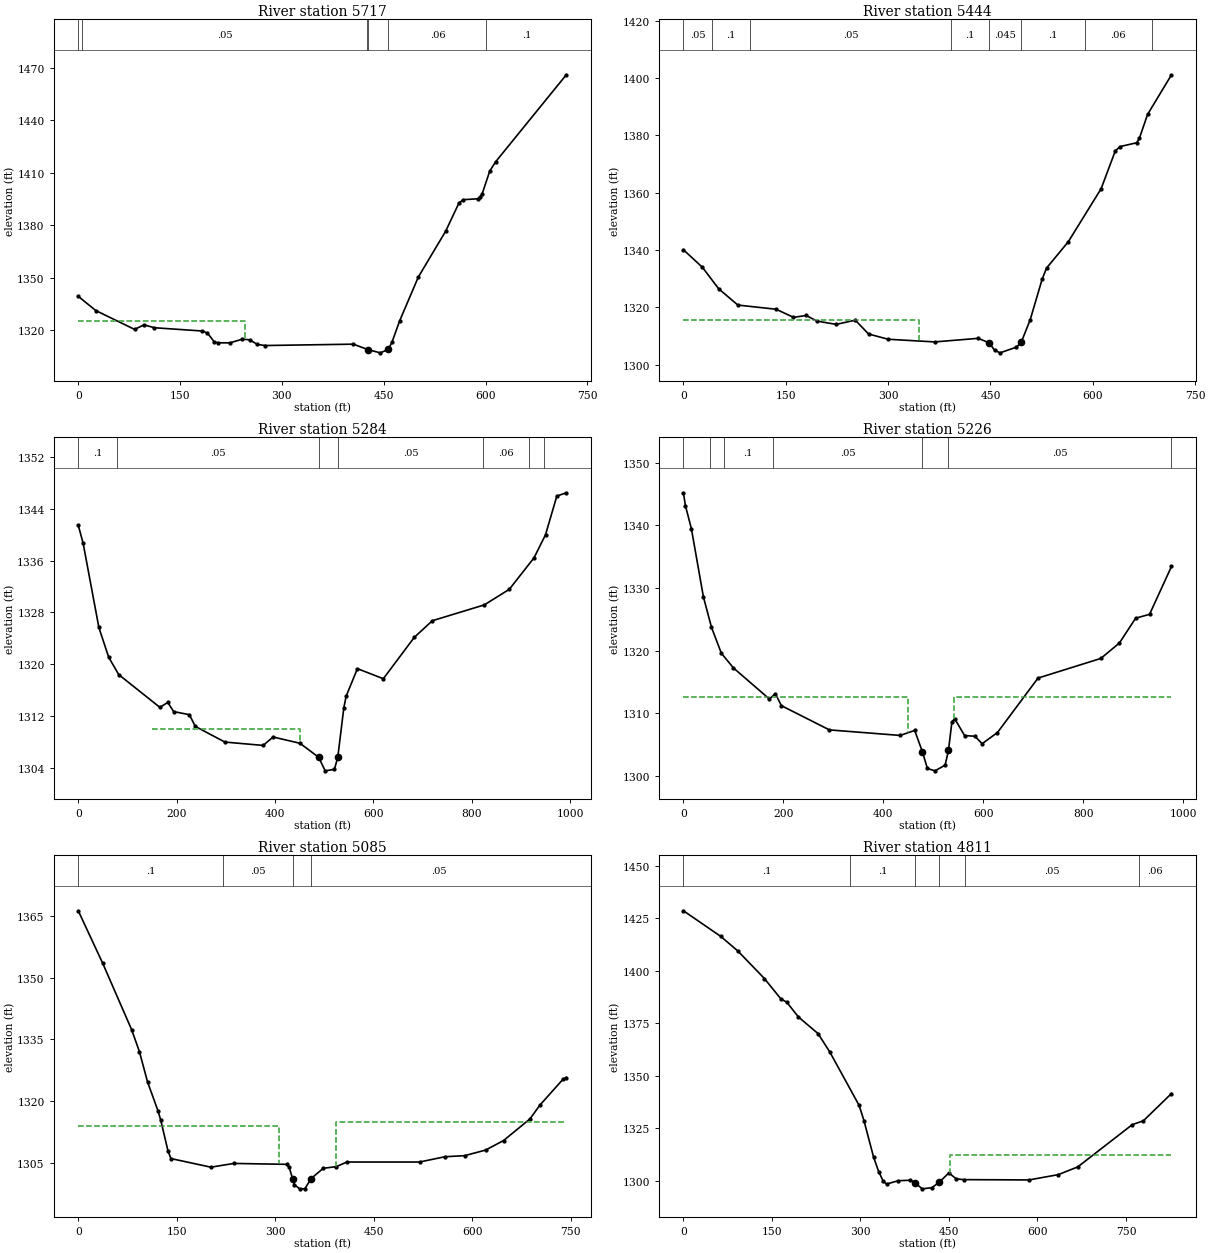
Type RM Length L Ch R = 1 ,5717    ,255.4,273.4,290.6
XS GIS Cut Line= 3
2470834.29559128669731.1683720332470887.31843738669912.972749275
2471252.18522869670296.887602167
#Sta/Elev= 30
       0  1339.3    25.9 1331.17      83 1320.42    96.9 1323.02   112.2 1321.36
     183 1319.49   190.3 1318.33   200.2 1313.35     206 1312.75   223.4 1312.72
   241.7 1314.83   252.6 1314.45   263.9 1311.81   275.2 1311.19   405.4 1311.97
   426.6 1308.86     445 1307.01   456.9 1308.99   462.4 1313.35   473.5 1325.31
     501 1350.36   541.2 1376.53     561 1392.81   567.3 1394.58   589.3 1395.13
   592.1 1396.23   594.9 1397.77   606.2 1410.92   614.7 1416.18     719 1466.01
#Mann= 6 ,-1 , 0
       0      .1       0    5.85     .05       0  425.18      .1       0
   426.6    .045       0   456.9     .06       0  601.26      .1       0
#XS Ineff= 2 , 0
           246.1 1325.35
Permanent Ineff=
       F       F
Bank Sta=426.6,456.9
XS Rating Curve= 0 ,0
Exp/Cntr=0.3,0.1

Type RM Length L Ch R = 1 ,5444    ,146.9,159.6,187
XS GIS Cut Line= 2
2470798.19832052669743.201193115 2470829.5548064670457.867767072
#Sta/Elev= 30
       0 1340.12    27.7 1334.05    51.7 1326.51    79.8 1320.84   135.8 1319.39
   161.3 1316.56   179.9 1317.21   195.8 1315.25   223.9 1314.11   251.9 1315.58
   271.3 1310.76     300 1308.92   368.4 1307.99   432.1 1309.24   448.1 1307.66
   456.1 1305.09   464.1 1304.18   488.2 1306.18     495 1307.79   508.2 1315.66
   525.7 1329.79   532.2 1333.73   564.1 1342.93   612.3 1361.46   633.1 1374.67
   640.3 1376.15   664.3 1377.45   668.3    1379   680.3 1387.32   715.4 1401.17
#Mann= 8 ,-1 , 0
       0     .05       0   41.44      .1       0   97.58     .05       0
  391.98      .1       0   448.1    .045       0     495      .1       0
  588.25     .06       0  686.38      .1       0
#XS Ineff= 2 , 0
          345.93 1315.63
Permanent Ineff=
       F       F
Bank Sta=448.1,495
XS Rating Curve= 0 ,0
Exp/Cntr(USF)=0,0
Exp/Cntr=0.5,0.3

Type RM Length L Ch R = 1 ,5284    ,46.5,58.6,58
XS GIS Cut Line= 4
2470731.33543548669773.0326836432470745.73843375670168.936625023
2470568.36102072670310.909793267 2470385.8789413670631.705562797
#Sta/Elev= 30
       0 1341.48     9.9  1338.7    41.9 1325.68    61.9 1321.07    82.3 1318.39
     166 1313.32     182 1314.09     194 1312.67     226 1312.19     238 1310.38
   298.1 1307.96   375.9 1307.44   396.2 1308.74   450.9 1307.77   488.9  1305.6
   502.1 1303.51   520.9 1303.74   527.7 1305.62   540.1  1313.3   544.8 1315.06
   567.6 1319.31   620.3 1317.75   683.2 1324.14     720 1326.72   825.8 1329.17
   876.4 1331.57   926.7 1336.44   950.1 1340.01   973.1 1345.99   992.4  1346.5
#Mann= 7 ,-1 , 0
       0      .1       0   78.31     .05       0   488.9    .045       0
   527.7     .05       0  823.24     .06       0  916.24     .05       0
   947.8     .06       0
#XS Ineff= 3 ,-1
     150     450    1310     450     474    1305     532     600    1307
Permanent Ineff=
       F       F       F
Bank Sta=488.9,527.7
XS Rating Curve= 0 ,0
Exp/Cntr=0.5,0.3

Type RM Length L Ch R = 1 ,5226    ,166.7,141,113.7
XS GIS Cut Line= 4
2470704.24577586 669775.009162712470719.38848043670143.108593285
2470534.22849086670278.8227004842470341.21453906670604.642527838
#Sta/Elev= 30
       0  1345.2     3.9 1343.16    15.9 1339.47    39.9 1328.61    56.1 1323.74
    75.9  1319.6     100 1317.26     172  1312.3     184 1313.15     196 1311.24
   292.1 1307.37   433.7 1306.49   462.8 1307.28   478.3 1303.86   488.2 1301.22
   503.4 1300.84   523.7 1301.75   530.4 1304.11   537.2 1308.62   542.8 1309.16
   562.6 1306.47   583.4 1306.36   597.7 1305.17   628.4 1306.95   709.6 1315.64
   835.2 1318.77   872.4 1321.23   904.9 1325.19   932.8 1325.81   976.7 1333.45
#Mann= 7 ,-1 , 0
       0      .1       0   52.92     .05       0   80.49      .1       0
  178.65     .05       0   478.3    .045       0   530.4     .05       0
  974.93     .06       0
#XS Ineff= 2 , 0
          448.54  1312.6  541.96         1312.63
Permanent Ineff=
       F       F
Bank Sta=478.3,530.4
XS Rating Curve= 0 ,0
Exp/Cntr=0.5,0.3

Type RM Length L Ch R = 1 ,5085    ,278,273.7,268.5
XS GIS Cut Line= 3
2470470.57443082669869.6967180112470472.56577397670303.809526099
2470323.21503725670574.632195365
#Sta/Elev= 30
       0 1366.18    37.2 1353.47    81.4 1337.32    93.2 1332.02   105.5 1324.71
   121.6 1317.62   125.6 1315.46   136.7 1307.96   141.2 1306.12     202 1304.03
   237.2 1304.94   317.2 1304.72   321.2 1304.09   326.5  1301.2   329.2  1299.8
   337.2 1298.78   345.2  1298.8   354.7 1301.27   373.2 1303.76   393.2 1304.17
   409.2 1305.28   519.9 1305.28   558.4 1306.56   588.4 1306.82   620.4 1308.17
   647.8 1310.49     688 1315.72   702.9 1319.02   739.1 1325.47   743.4 1325.75
#Mann= 4 ,-1 , 0
       0      .1       0   219.8     .05       0   326.5    .045       0
   354.7     .05       0
#XS Ineff= 2 , 0
          306.23 1313.95  392.63         1314.93
Permanent Ineff=
       F       F
Bank Sta=326.5,354.7
XS Rating Curve= 0 ,0
Exp/Cntr(USF)=0,0
Exp/Cntr=0.3,0.1

Type RM Length L Ch R = 1 ,4811    ,300.1,292,278.7
XS GIS Cut Line= 3
     2470108.814      669861.537     2470204.366      670257.785
     2470304.772      670665.157
#Sta/Elev= 30
       0 1428.61    63.1 1416.43    91.9 1409.54   137.2 1396.34   165.2 1386.62
   175.1 1385.06   194.8 1378.05   228.2 1370.08   248.3 1361.22   297.8 1335.87
   305.9 1328.68   322.3 1311.24   330.9 1304.34   338.8  1299.7   344.2  1298.4
   363.5 1299.98   384.1 1300.26   392.3 1299.14   404.6 1296.14   421.1 1296.67
   433.5 1299.28   449.9 1303.73   462.3 1300.91   474.7 1300.53   585.7 1300.38
   635.2  1302.9   668.3 1306.59   760.8 1326.74   779.5 1328.54   827.2 1341.56
#Mann= 6 ,-1 , 0
       0      .1       0  281.89      .1       0   392.3    .045       0
   433.5      .1       0  477.66     .05       0   771.4     .06       0
#XS Ineff= 2 , 0
                          451.98         1312.04
Permanent Ineff=
       F       F
Bank Sta=392.3,433.5
XS Rating Curve= 0 ,0
Exp/Cntr=0.3,0.1

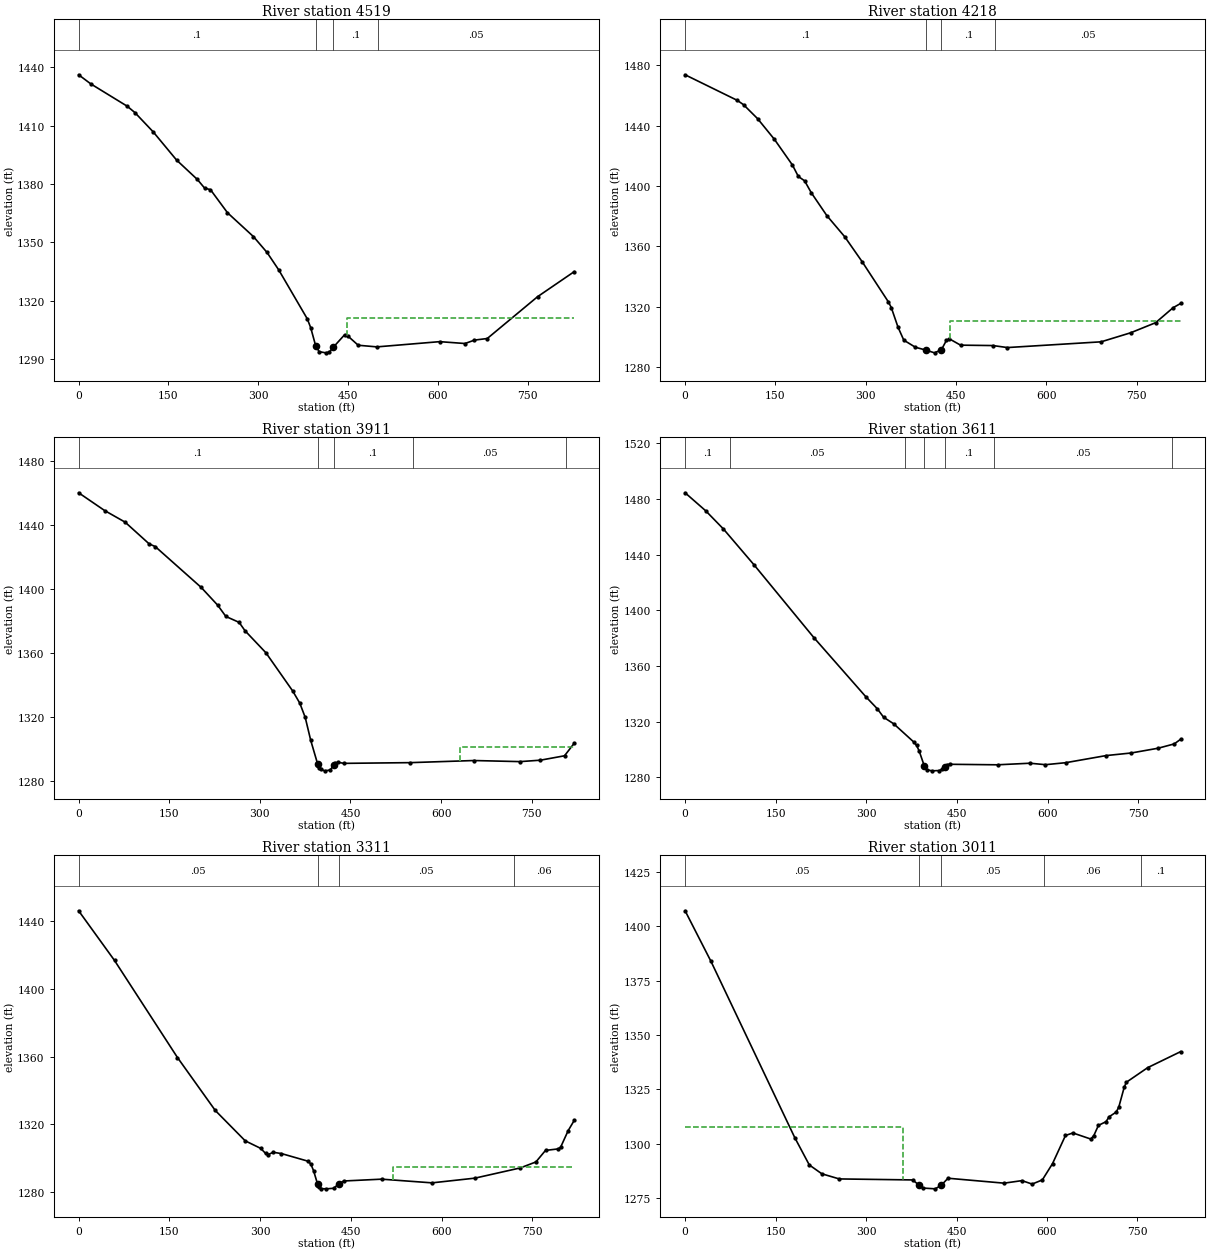
Type RM Length L Ch R = 1 ,4519    ,297.2,300.5,301.2
XS GIS Cut Line= 2
2469689.53038566670077.412614345     2470229.185      670705.213
#Sta/Elev= 30
       0 1436.07    20.3 1431.39    81.1 1419.93    93.9 1416.68   124.6 1406.73
   163.6 1392.26   198.2 1382.32   210.5 1377.83   220.3 1377.02   248.7 1365.18
   292.1 1352.91   314.8 1344.76   334.3 1335.81     382 1310.66   387.7 1306.15
   396.2 1296.61   401.9 1293.79     413 1293.19   418.9  1293.6   425.3 1296.01
   444.4 1302.49   450.1 1301.75   467.1 1297.09   498.3 1296.25   603.2 1298.94
   645.5 1297.98   661.3 1299.73   682.7 1300.55   766.8 1322.05   827.9 1334.89
#Mann= 4 ,-1 , 0
       0      .1       0   396.2    .045       0   425.3      .1       0
  499.85     .05       0
#XS Ineff= 2 , 0
                          447.78         1311.06
Permanent Ineff=
       F       F
Bank Sta=396.2,425.3
XS Rating Curve= 0 ,0
Exp/Cntr=0.3,0.1

Type RM Length L Ch R = 1 ,4218    ,315.2,307.5,297.9
XS GIS Cut Line= 2
     2469519.882      670259.012     2469979.538      670941.303
#Sta/Elev= 30
       0  1473.6    86.7 1456.64    97.1 1453.76   120.4 1444.52   148.3 1430.83
   178.3 1413.77     188 1406.24   198.4 1403.37   209.5 1395.47   235.4 1380.28
   265.1 1366.28   294.1  1349.7   337.5 1323.18   342.3 1319.45   353.5 1306.42
   363.1 1297.82   382.4 1293.13   399.6 1291.27   414.1 1289.44   425.6 1291.54
   433.9 1297.73   438.8 1298.69   457.3 1294.53   511.1 1294.26   535.1 1292.94
   690.7 1296.74   739.7 1302.72   781.2 1309.41   810.1 1319.31   822.7 1322.15
#Mann= 4 ,-1 , 0
       0      .1       0   399.6    .045       0   425.6      .1       0
  515.02     .05       0
#XS Ineff= 2 , 0
                          440.36         1310.73
Permanent Ineff=
       F       F
Bank Sta=399.6,425.6
XS Rating Curve= 0 ,0
Exp/Cntr=0.3,0.1

Type RM Length L Ch R = 1 ,3911    ,302.4,300,295
XS GIS Cut Line= 3
     2469183.609      670622.695     2469545.123      670815.115
     2469903.473      671015.988
#Sta/Elev= 30
       0 1460.18      43 1449.09      77 1441.82   116.8 1428.24   126.7 1426.62
   202.9 1401.06   230.2 1389.96   243.7 1382.94   265.7 1379.23   275.4 1374.02
     310 1360.26   354.4 1336.36   366.1 1328.78   375.1 1319.86   384.2 1305.54
   395.8 1290.57   397.8 1288.49   400.5 1287.39   407.6  1286.5   416.4 1287.01
   422.3 1289.99   425.1  1291.4   429.7 1291.84   438.9 1291.17     549 1291.62
   654.3 1292.94   730.8 1292.26   764.5 1293.16   804.3  1295.9   820.3 1303.69
#Mann= 5 ,-1 , 0
       0      .1       0   395.8    .045       0   422.3      .1       0
   553.3     .05       0  807.04     .06       0
#XS Ineff= 2 , 0
                          631.63         1301.51
Permanent Ineff=
       F       F
Bank Sta=395.8,422.3
XS Rating Curve= 0 ,0
Exp/Cntr=0.3,0.1

Type RM Length L Ch R = 1 ,3611    ,299.7,300,298.7
XS GIS Cut Line= 3
      2469054.34      670966.851     2469443.767      671093.146
     2469836.964      671211.159
#Sta/Elev= 30
       0 1484.49    34.1 1471.54    63.5 1458.43     114 1432.74   213.1 1380.39
   298.8 1338.03     318 1329.29   328.4  1323.2   345.2 1318.46   378.9 1305.17
   383.1 1302.89   387.3 1298.91   395.7 1288.29   399.9 1285.47   408.3 1284.67
   420.9 1284.89     425  1285.7   429.2 1287.62   429.2 1287.64   433.4 1289.04
   437.6 1289.38   516.9 1289.01   570.6 1290.14   596.3 1289.09   629.7 1290.52
   696.5 1295.63   738.3 1297.51   782.6 1300.92   809.3 1304.02   819.9 1307.36
#Mann= 7 ,-1 , 0
       0      .1       0   73.88     .05       0  363.46      .1       0
   395.7    .045       0   429.2      .1       0  511.05     .05       0
  805.64     .06       0
Bank Sta=395.7,429.2
XS Rating Curve= 0 ,0
Exp/Cntr=0.3,0.1

Type RM Length L Ch R = 1 ,3311    ,299.3,300,300.3
XS GIS Cut Line= 3
     2468973.746      671266.733     2469367.509      671380.696
     2469760.231      671496.037
#Sta/Elev= 30
       0 1446.21    59.3 1416.85   163.4 1359.44   225.9 1328.14   275.4 1310.19
   300.9 1305.75   309.2 1302.71   313.4 1302.09   321.7 1303.42   335.3 1302.66
     380 1298.07   384.1 1296.25   388.3 1292.64   394.9 1284.75   396.6 1283.09
   400.8 1281.93   409.1 1281.81   421.6 1282.14   430.4 1284.89   438.3 1286.45
   500.8 1287.53   584.2 1285.35   655.1 1288.13     730 1294.17   755.9  1297.7
   771.8 1304.53   792.7 1305.42   796.8 1306.41   809.3 1316.24   819.2 1322.22
#Mann= 4 ,-1 , 0
       0     .05       0   394.9    .045       0   430.4     .05       0
   719.3     .06       0
#XS Ineff= 2 , 0
                          519.56         1294.76
Permanent Ineff=
       F       F
Bank Sta=394.9,430.4
XS Rating Curve= 0 ,0
Exp/Cntr=0.3,0.1

Type RM Length L Ch R = 1 ,3011    ,298.3,300,299.4
XS GIS Cut Line= 3
     2468893.596       671549.57     2469288.342      671668.359
     2469675.791      671800.501
#Sta/Elev= 30
       0 1407.11      43 1383.78   181.8 1302.75   205.9 1290.17   226.7 1286.09
   255.6 1283.73   377.1 1283.27   387.3 1281.04   394.1 1279.54   414.8 1279.17
   424.9 1280.88   435.9 1284.05   528.9 1281.78   558.5 1282.95   575.4 1281.36
   592.3 1283.28   609.2 1290.78   630.7 1303.73     643 1304.88   672.6 1302.08
   677.7  1303.7   685.3 1308.37   697.9 1310.07   702.9  1312.3   714.8 1314.49
   719.1 1316.83   728.1 1325.97   731.7 1328.23     767 1334.94   821.6  1342.3
#Mann= 5 ,-1 , 0
       0     .05       0   387.3    .045       0   424.9     .05       0
  594.27     .06       0  756.58      .1       0
#XS Ineff= 2 , 0
          361.94 1307.68
Permanent Ineff=
       F       F
Bank Sta=387.3,424.9
XS Rating Curve= 0 ,0
Exp/Cntr=0.3,0.1

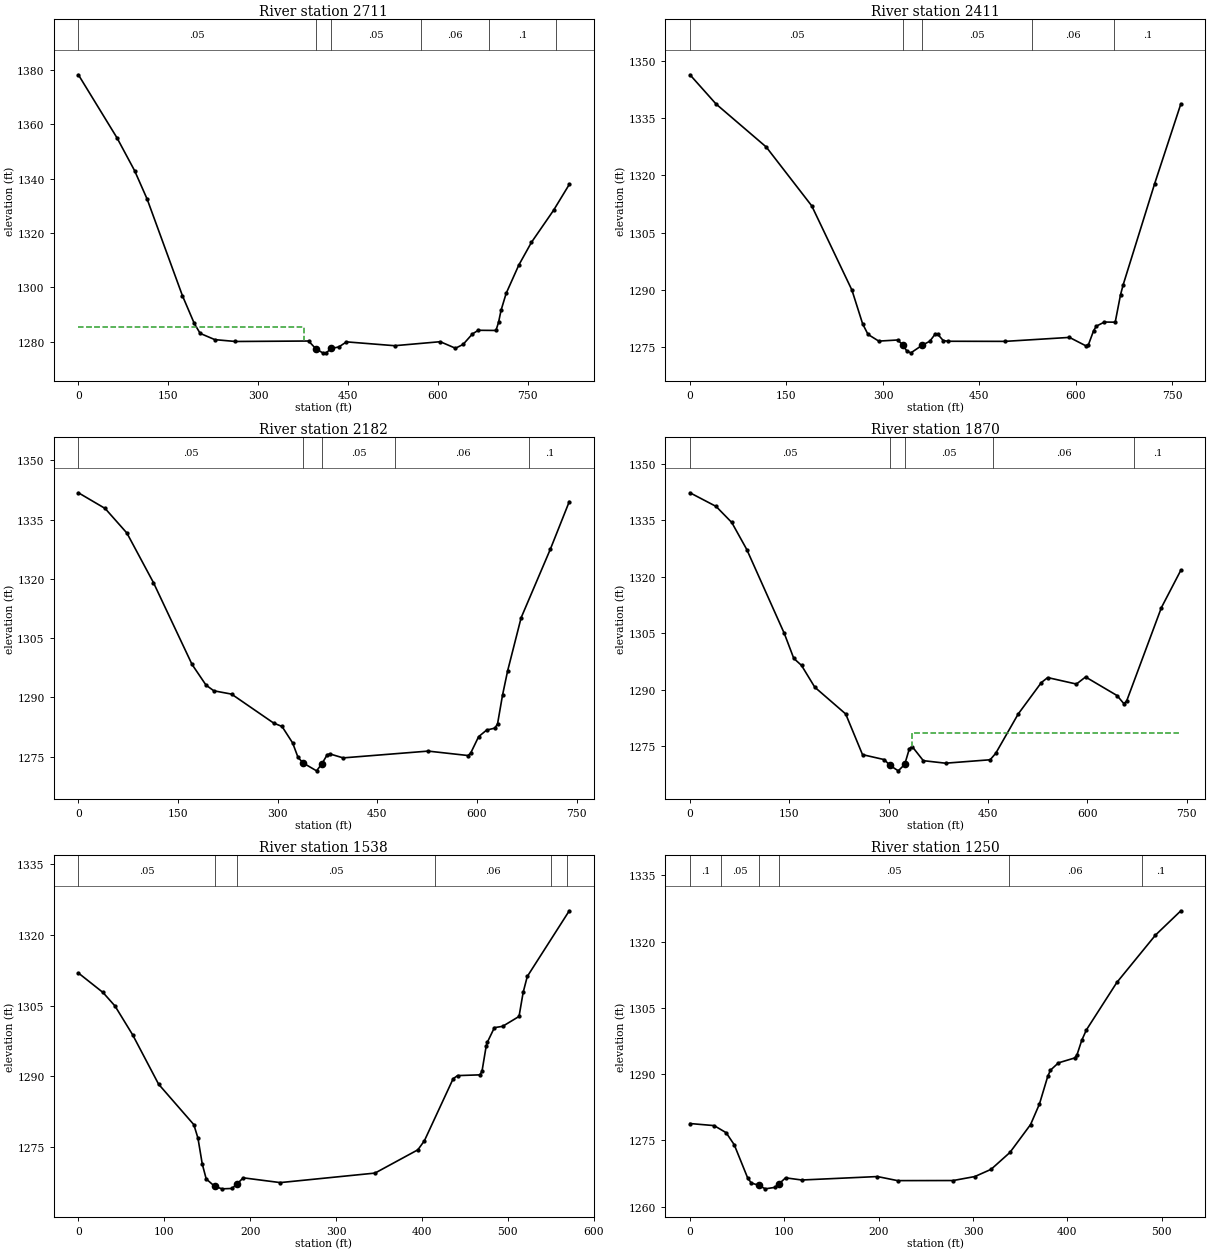
Type RM Length L Ch R = 1 ,2711    ,300.2,300,299.1
XS GIS Cut Line= 3
     2468805.633       671824.03     2469195.292       671951.61
     2469582.489      672084.632
#Sta/Elev= 30
       0  1378.1    64.3 1354.99    93.8  1342.9   114.8 1332.42   173.7 1296.96
   193.4 1286.81   203.2 1283.15   227.7 1280.85   262.1 1280.17   384.2 1280.34
   396.3 1277.52   407.7    1276   413.7 1276.02   422.1  1277.6   434.8 1278.17
   447.5 1280.03   527.9 1278.62     604 1280.09   629.4 1277.69   642.1 1279.08
   657.7 1282.93   667.4 1284.28     697 1284.22   701.3 1287.17   705.5 1291.61
     714 1297.82   735.1 1308.21   756.3 1316.59   793.1 1328.32   819.4 1337.84
#Mann= 6 ,-1 , 0
       0     .05       0   396.3    .045       0   422.1     .05       0
  572.41     .06       0  685.07      .1       0  797.72      .1       0
#XS Ineff= 2 , 0
          376.64  1285.4
Permanent Ineff=
       F       F
Bank Sta=396.3,422.1
XS Rating Curve= 0 ,0
Exp/Cntr=0.3,0.1

Type RM Length L Ch R = 1 ,2411    ,233.1,228.5,222.2
XS GIS Cut Line= 3
2468785.03524906672138.240850285     2469115.365      672234.877
     2469516.547      672355.941
#Sta/Elev= 30
       0 1346.29    40.6 1338.63   118.5  1327.4   189.3 1311.99   251.8 1289.94
   268.5 1281.08   276.8 1278.35   293.5  1276.6   322.7 1276.89     331 1275.62
   337.2 1273.96   343.5 1273.53   361.2 1275.54   372.8 1276.56   381.1 1278.41
   385.3 1278.36   393.7 1276.75   401.5 1276.56   489.8 1276.53     590 1277.57
   615.1  1275.4   619.3 1275.58   627.6 1279.35   631.8 1280.52   644.4 1281.59
   661.1 1281.55   669.4 1288.75   673.6  1291.4   722.4 1317.78   763.2 1338.69
#Mann= 5 ,-1 , 0
       0     .05       0     331    .045       0   361.2     .05       0
  531.18     .06       0  659.81      .1       0
Bank Sta=331,361.2
XS Rating Curve= 0 ,0
Exp/Cntr=0.3,0.1

Type RM Length L Ch R = 1 ,2182    ,284.4,312.4,330.2
XS GIS Cut Line= 3
2468765.67225518672366.1029778772468948.11131919  672457.2203042
2469483.28459406 672463.73130885
#Sta/Elev= 30
       0 1341.82    40.2 1337.85      73 1331.62     113 1319.06   171.1 1298.33
   192.2 1293.08   203.9 1291.65   230.6 1290.81     294 1283.47   306.6 1282.61
   322.6 1278.43   330.7 1274.77   338.5 1273.35   358.6 1271.37   366.6 1273.15
   374.6 1275.44   378.6 1275.66   398.6 1274.65   526.6 1276.37   586.6 1275.25
   590.6 1275.85   602.6 1280.03   614.6 1281.69   627.1  1282.2   631.1 1283.28
   638.6 1290.56   646.3 1296.72   666.6 1310.16   710.6 1327.53   739.1 1339.59
#Mann= 5 ,-1 , 0
       0     .05       0   338.5    .045       0   366.6     .05       0
  477.44     .06       0  679.08      .1       0
Bank Sta=338.5,366.6
XS Rating Curve= 0 ,0
Exp/Cntr=0.3,0.1

Type RM Length L Ch R = 1 ,1870    ,341.4,331.7,318.9
XS GIS Cut Line= 3
2468757.19096201672387.3930104732468880.56573479 672496.18594509
2469057.90739265673044.969648254
#Sta/Elev= 30
       0 1342.35    39.4 1338.73    63.1 1334.46    85.8 1327.27   142.4 1305.01
   156.7 1298.39   168.4 1296.52   188.4 1290.74   235.1 1283.63   260.5 1272.83
   293.4 1271.51   301.8 1269.99   314.5 1268.53   324.21270.237   331.3 1274.44
   335.5 1274.98   352.3 1271.23   385.9 1270.56   453.2 1271.47   461.6 1273.17
   495.6 1283.63   530.5 1291.96   540.1 1293.29   583.5 1291.57   597.3 1293.45
   644.9 1288.51     655 1286.39   659.2 1287.01   711.8 1311.87   741.2  1321.8
#Mann= 5 ,-1 , 0
       0     .05       0   301.8    .045       0   324.2     .05       0
  458.06     .06       0  670.37      .1       0
#XS Ineff= 2 , 0
                          335.51         1278.51
Permanent Ineff=
       F       F
Bank Sta=301.8,324.2
XS Rating Curve= 0 ,0
Exp/Cntr=0.3,0.1

Type RM Length L Ch R = 1 ,1538    ,287.3,288.2,288.4
XS GIS Cut Line= 2
2468558.59323436672763.429633255 2469035.5468442673078.301090635
#Sta/Elev= 30
       0 1311.87    28.6 1307.76    42.6  1304.9    63.2 1298.79    93.4 1288.36
   134.4 1279.81   139.2 1276.95   144.2  1271.5   148.8 1268.33   158.7 1266.76
   167.2 1266.24   178.7 1266.32   184.5 1267.23   191.9 1268.57     235 1267.56
   345.3 1269.57   395.2 1274.49   402.8  1276.4   436.3 1289.52   441.4 1290.18
   467.4 1290.34   469.9 1291.11   474.7 1296.37   476.1 1297.23   484.3 1300.32
   493.9  1300.6     513 1302.69   517.8 1307.78   522.6 1311.14   571.5 1325.03
#Mann= 6 ,-1 , 0
       0     .05       0   158.7    .045       0   184.5     .05       0
  415.54     .06       0  550.55      .1       0  568.65     .12       0
Bank Sta=158.7,184.5
XS Rating Curve= 0 ,0
Exp/Cntr=0.3,0.1

Type RM Length L Ch R = 1 ,1250    ,178.6,176.6,173.5
XS GIS Cut Line= 2
  2468470.007877673042.2071855022468892.01391609 673346.62640256
#Sta/Elev= 30
       0 1278.81    25.6 1278.34    38.3 1276.74    46.9 1274.01    61.2 1266.46
      65 1265.36    72.91264.823    79.8 1264.03    89.7 1264.35    94.6  1265.2
   101.3 1266.52   118.5 1266.03   198.7 1266.81     220 1265.89   278.9 1265.91
   301.9 1266.81   319.1 1268.44   339.1 1272.26     361 1278.58   370.4 1283.23
   379.2 1289.49   382.1 1290.89   390.5 1292.54   407.9 1293.66   410.3 1294.42
   415.2 1297.62   420.1 1299.98   452.4 1310.73   493.4 1321.46   520.3 1326.96
#Mann= 6 ,-1 , 0
       0      .1       0   32.73     .05       0    72.9    .045       0
    94.6     .05       0  338.23     .06       0  478.72      .1       0
Bank Sta=72.9,94.6
XS Rating Curve= 0 ,0
Exp/Cntr(USF)=0,0
Exp/Cntr=0.3,0.1

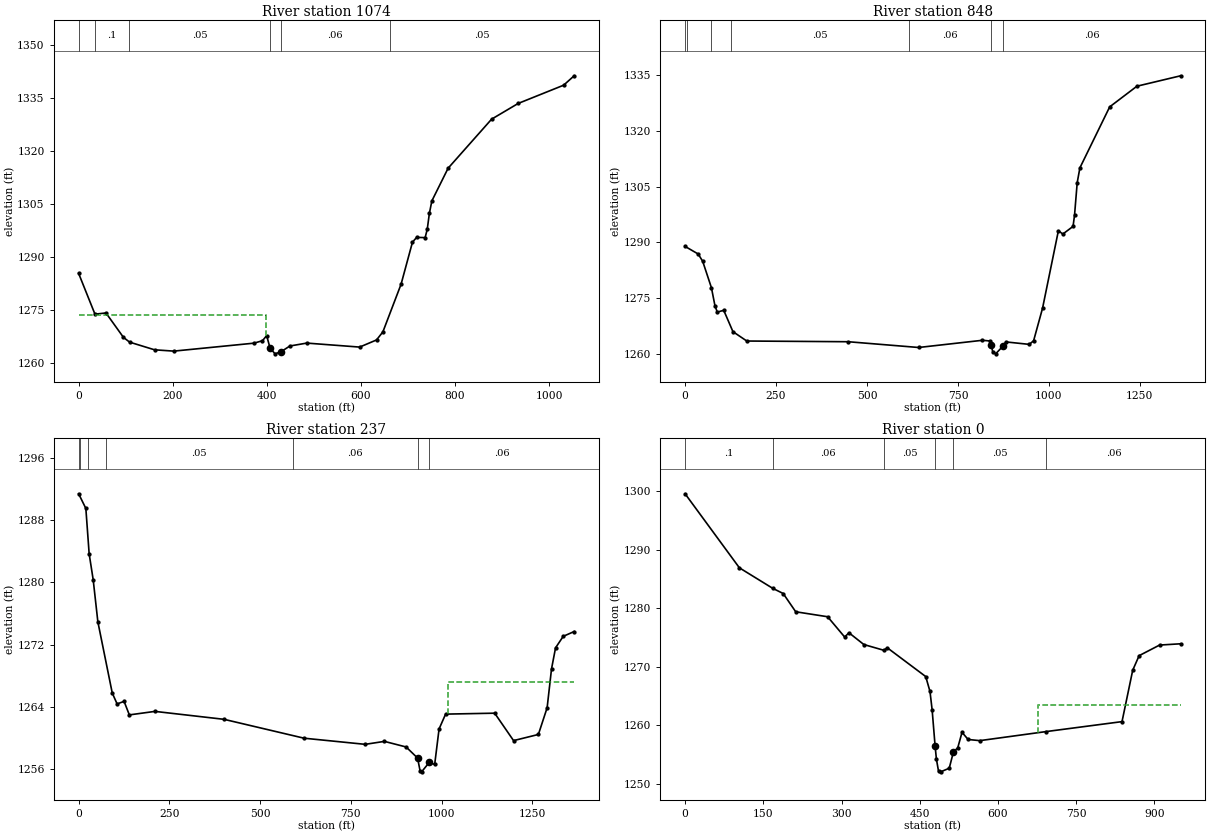
Type RM Length L Ch R = 1 ,1074    ,230,226,217.8
XS GIS Cut Line= 4
2468401.46938851672876.9131956872468337.42798043 673183.22870434
2468753.26905668673395.3235789942469025.12651371673425.309639491
#Sta/Elev= 30
       0 1285.28    34.7 1273.75    58.1 1274.09    95.2  1267.2   108.3 1265.84
   161.4 1263.67   202.3  1263.3   372.8 1265.55   390.8 1266.25   399.7 1267.68
   406.81264.183   417.5 1262.53     4301263.122   449.1 1264.75     485 1265.57
   597.3 1264.44   633.2 1266.46   646.7 1268.74   685.4 1282.23   709.6 1294.12
   718.5 1295.46   736.5  1295.4     741 1297.74   745.5 1302.23   750.8 1305.78
   785.3 1315.02   877.8  1328.9   934.2 1333.34  1030.8  1338.5  1053.3 1341.17
#Mann= 6 ,-1 , 0
       0     .05       0   35.12      .1       0  107.01     .05       0
   406.8    .045       0     430     .06       0  661.37     .05       0
#XS Ineff= 2 , 0
          398.25 1273.53
Permanent Ineff=
       F       F
Bank Sta=406.8,430
XS Rating Curve= 0 ,0
Exp/Cntr=0.3,0.1

Type RM Length L Ch R = 1 ,848     ,572.2,610.6,648.3
XS GIS Cut Line= 3
 2468414.2893714672818.3483245742468207.76524903673425.983675024
2468925.36462442673488.025309651
#Sta/Elev= 30
       0 1288.93    35.9 1286.89    48.3 1284.94    72.4  1277.8      82 1272.99
    88.4 1271.25   106.2 1271.73   131.5 1265.98   169.6 1263.46   448.4 1263.27
   641.8 1261.72   817.4 1263.66   837.5 1263.47   841.2 1262.34   845.5 1260.62
   853.5 1260.01   873.6 1262.07   881.6 1263.22   945.9 1262.56   957.9 1263.54
   982.5 1272.31    1026 1293.16  1038.2 1292.26  1066.3 1294.32  1070.4 1297.36
  1077.7 1306.09  1085.1 1310.08    1167  1326.5  1241.8 1332.06    1362 1334.87
#Mann= 7 ,-1 , 0
       0      .1       0    5.78     .05       0   70.16      .1       0
  127.06     .05       0     615     .06       0   841.2    .045       0
   873.6     .06       0
Bank Sta=841.2,873.6
XS Rating Curve= 0 ,0
Exp/Cntr(USF)=0,0
Exp/Cntr=0.3,0.1

Type RM Length L Ch R = 1 ,237     ,237,237,237
XS GIS Cut Line= 4
2468410.24511699672774.8244438152467907.33492167673526.127117478
2467912.48562558673632.9212873862468264.80307131 673669.05384024
#Sta/Elev= 30
       0 1291.41    19.9 1289.52      29 1283.68    40.1 1280.35      53 1274.92
    92.6 1265.77     106 1264.36   125.2 1264.69   139.7 1262.95   210.2  1263.4
   400.5 1262.38     621 1259.95   789.5 1259.16   842.4 1259.54   902.2 1258.82
   933.81257.394   940.9  1255.7   944.9 1255.62   966.1 1256.84   980.9 1256.57
     993 1261.14    1011 1263.05  1146.2 1263.17  1198.2 1259.64  1266.6 1260.43
  1290.7 1263.87  1302.8 1268.87  1313.9 1271.58    1335 1273.06  1365.2 1273.68
#Mann= 7 ,-1 , 0
       0      .1       0     2.6     .05       0    26.5      .1       0
    74.1     .05       0   590.3     .06       0   933.8    .045       0
   966.1     .06       0
#XS Ineff= 2 , 0
                          1018.4         1267.24
Permanent Ineff=
       F       F
Bank Sta=933.8,966.1
XS Rating Curve= 0 ,0
Exp/Cntr(USF)=0,0
Exp/Cntr=0.3,0.1

Type RM Length L Ch R = 1 ,0       ,,,
XS GIS Cut Line= 3
2467366.61293367673821.6782716892467589.80055687 673821.45841723
2468300.59228438673668.721803561
#Sta/Elev= 30
       0 1299.54   104.1 1286.89   168.1 1283.38   188.1  1282.5   212.1 1279.38
   273.3 1278.53     306 1275.06   314.2 1275.79   342.8 1273.78   381.1  1272.8
   387.8 1273.22   461.4 1268.31   469.6 1265.76   473.7 1262.62  479.371256.461
   481.9  1254.2     486 1252.12   490.1 1252.03   506.5 1252.65   514.6 1255.45
   522.8 1256.13     531 1258.78   542.7 1257.56     565 1257.36   692.4 1258.91
   837.8 1260.61   858.3 1269.39   870.6 1271.88   909.8 1273.69 950.205 1273.91
#Mann= 6 ,-1 , 0
       0      .1       0   168.1     .06       0   381.1     .05       0
  479.37    .045       0   514.6     .05       0   692.4     .06       0
#XS Ineff= 2 , 0
                          675.94         1263.51
Permanent Ineff=
       F       F
Bank Sta=479.37,514.6
XS Rating Curve= 0 ,0
Exp/Cntr(USF)=0,0
Exp/Cntr=0.3,0.1
LCMann Table=0

Chan Stop Cuts=-1
Use User Specified Reach Order=0
Composite Channel Slope=5